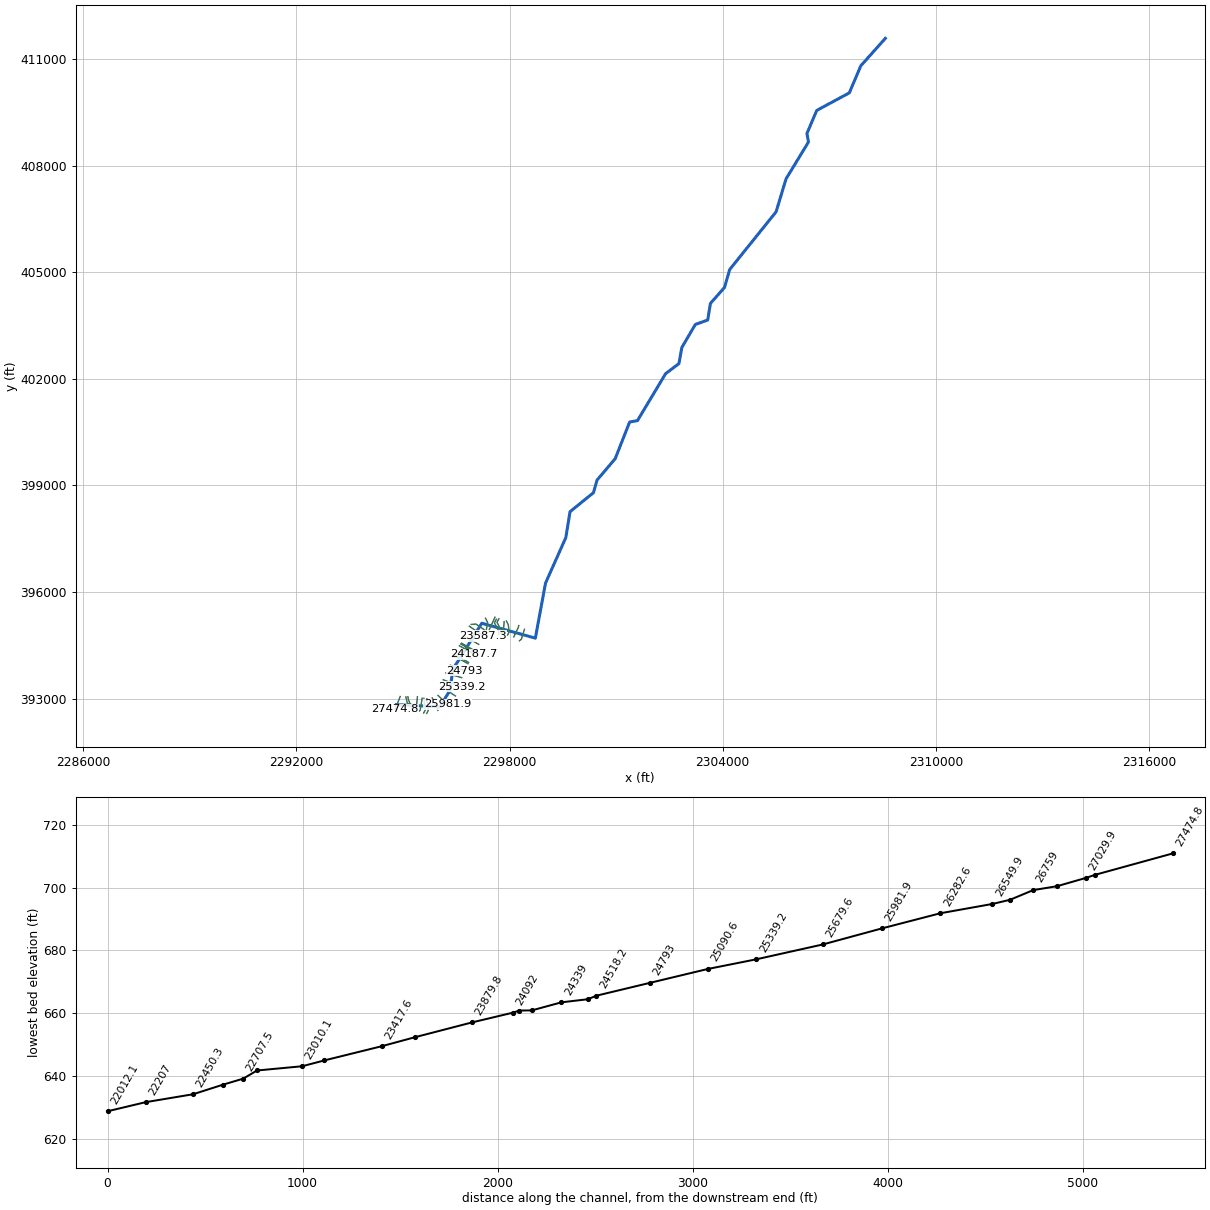
--- LONGHOLLOW.prj (project) ---

Proj Title=LONGHOLLOW
Current Plan=p01
Default Exp/Contr=0,0
English Units
Geom File=g01
Flow File=f01
Plan File=p01
BEGIN DESCRIPTION:
END DESCRIPTION:
DSS Export Rating Curves= 0
DSS Export Rating Curve Sorted= 0
DSS Export Volume Flow Curves= 0
DXF OffsetX= 0
DXF OffsetY= 0
DXF ScaleX= 0
DXF ScaleY= 0

--- LONGHOLLOW.p01 (plan) ---

Plan Title=Floodplain
Program Version=4.00
Geom File=g01
Flow File=f01
K Sum by GR=0
Std Step Tol=0.01
Critical Tol=0.01
Num of Std Step Trials=20
Max Error Tol=0.3
Flow Tol Ratio=0.001
Split Flow NTrial=30
Split Flow Tol=0.02
Split Flow Ratio=0.02
Log Output Level=0
Friction Slope Method=1
Unsteady Friction Slope Method=2
Unsteady Bridges Friction Slope Method=1
Global Log Level=0
CheckData=False
Run HTab=0
Run UNet=0
Run PostProcess=0
UNET Theta=0
UNET Theta Warmup=0
UNET ZTol=0
UNET ZSATol=0
UNET MxIter=0
UNET MaxInSteps=0
UNET DtIC=0
UNET DtMin=0
UNET MaxCRTS=0
UNET WFStab=0
UNET SFStab=0
UNET WFX=0
UNET SFX=0
UNET DSS MLevel=0
UNET DZMax Abort=0
UNET Convert EG Bridges=0
UNET Use Existing IB Tables=0
UNET Froude Limit=0
UNET Froude Power=0
Write IC File=0
Echo Input=False
Echo Output=False
Write Detailed=0

--- LONGHOLLOW.f01 (steady flow) ---

Flow Title=NFF Regression Equation
Program Version=4.00
Number of Profiles=1
Profile Names=P100yr
River Rch & RM=LONGHOLLOW,Main      ,27474.8
530.7852
River Rch & RM=LONGHOLLOW,Main      ,26639.9
537.5564
River Rch & RM=LONGHOLLOW,Main      ,26282.6
631.1885
River Rch & RM=LONGHOLLOW,Main      ,24187.7
664.4534
River Rch & RM=LONGHOLLOW,Main      ,21819.8
734.4664
River Rch & RM=LONGHOLLOW,Main      ,21274.1
901.3978
River Rch & RM=LONGHOLLOW,Main      ,19969.1
929.8723
River Rch & RM=LONGHOLLOW,Main      ,15565.4
1014.589
River Rch & RM=LONGHOLLOW,Main      ,13683.9
1125.900
River Rch & RM=LONGHOLLOW,Main      ,13106.5
1181.563
River Rch & RM=LONGHOLLOW,Main      ,8780.7
1288.712
River Rch & RM=LONGHOLLOW,Main      ,5771.2
1423.165
River Rch & RM=LONGHOLLOW,Main      ,109.7
1539.892
Boundary for River Rch & Prof#=LONGHOLLOW,Main      ,1
Up Type=0
Dn Type=3
Dn Slope=0.003158

--- LONGHOLLOW.g01 (geometry) ---

Geom Title=USGS 10m DEM
Program Version=4.10

River Reach=LONGHOLLOW      ,Main
Reach XY= 30
     2294814.108      392835.889     2296038.093      392773.087
     2296317.088      393224.246     2296408.962      393836.488
     2297218.666      395124.673     2298726.998      394706.241
     2299013.295      396254.092     2299585.003      397534.708
     2299702.741      398262.873     2300363.513      398797.505
     2300463.139      399151.434     2300974.523      399753.411
     2301381.685      400785.763     2301600.818      400824.032
     2302392.716      402144.112      2302769.16      402429.525
     2302850.581      402881.591     2303230.137      403529.944
      2303578.96       403654.34     2303654.974      404120.992
     2304051.948        404571.3     2304199.809      405077.912
     2305504.304       406698.49     2305783.676      407623.712
     2306415.931      408662.122     2306372.421      408900.898
     2306648.436      409550.769     2307565.244      410043.662
     2307889.117      410806.385     2308579.943      411578.484

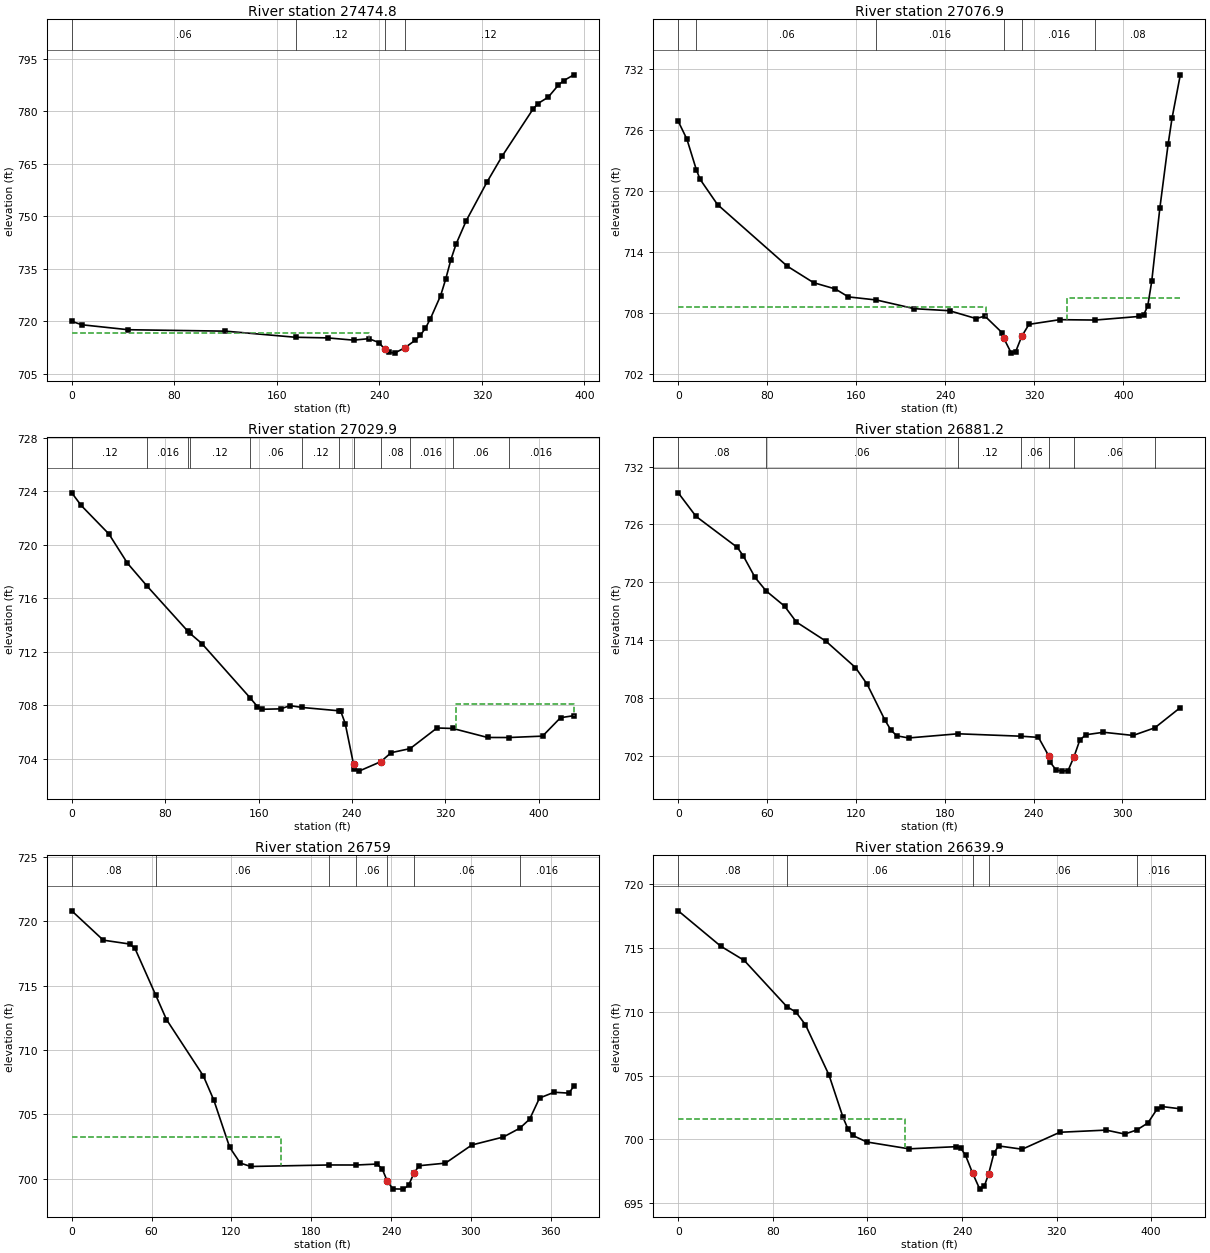
Type RM Length L Ch R = 1 ,27474.8 ,367.1,397.9,426.7
XS GIS Cut Line= 2
     2294921.865      393064.204     2294778.636      392699.621
#Sta/Elev= 30
       0  719.92       8  718.94      44  717.53   119.9  717.12  174.55715.3735
   199.8  715.19   219.8  714.55   231.8  714.97   239.8  713.83     244  712.01
   247.8  711.09   251.8  710.84   259.8  712.35   267.8  714.48   271.8  715.89
   275.8  717.88   279.8  720.68   287.8  727.31   291.8  732.08   295.8  737.58
   299.8  741.99   307.8  748.73   323.8  759.64   335.8  767.16   359.7   780.5
   363.7  782.18   371.7  783.99   379.7  787.47   383.7  788.71   391.7  790.38
#Mann= 4 ,-1 , 0
       0     .06       0  174.55     .12       0     244    .045       0
   259.8     .12       0
#XS Ineff= 2 , 0
          232.09  716.45
Permanent Ineff=
       F       F
Bank Sta=244,259.8
XS Rating Curve= 0 ,0
Exp/Cntr=0.3,0.1

Type RM Length L Ch R = 1 ,27076.9 ,43.6,47,57.2
XS GIS Cut Line= 4
     2295081.151      393053.413     2295120.344      392885.401
      2295293.13      392710.726     2295290.613      392677.892
#Sta/Elev= 30
       0  726.85     7.8  725.09   16.24722.0977    19.6  721.15    35.3  718.66
      98   712.6   121.6  710.98   141.2  710.36   152.9  709.58  178.15 709.275
   212.2  708.42   243.8  708.22   267.6  707.45   275.6  707.69   291.4  706.02
  292.68  705.49   299.3  704.05   303.3  704.21  308.73  705.71   315.2  706.88
   342.9  707.34  374.78707.3032   414.3  707.66   418.2  707.81   421.9  708.67
   425.5   711.1   432.8   718.3   440.2  724.57   443.8  727.18   451.2  731.42
#Mann= 6 ,-1 , 0
       0    .016       0   16.24     .06       0  178.15    .016       0
  292.68    .045       0  308.73    .016       0  374.78     .08       0
#XS Ineff= 2 , 0
          276.64  708.62  349.17          709.51
Permanent Ineff=
       F       F
Bank Sta=292.68,308.73
XS Rating Curve= 0 ,0
Exp/Cntr=0.3,0.1

Type RM Length L Ch R = 1 ,27029.9 ,174.2,148.7,114.9
XS GIS Cut Line= 5
     2295139.311      393056.017     2295155.804      392970.079
     2295200.335      392859.489      2295357.28      392734.836
     2295360.795      392712.245
#Sta/Elev= 30
       0   723.9       8  722.96    31.8  720.82    47.7  718.63    64.5 716.919
   99.62713.5208  101.15713.3869   111.4  712.62  152.49708.5801     159   707.9
     163   707.7   178.9  707.73   186.9  707.97  197.53707.8332  228.63707.5871
   230.3  707.57   234.2  706.63   241.3703.5923   242.1  703.26     246  703.07
   264.7  703.78   273.5  704.45  289.79704.7557   312.8   706.3  326.37706.2625
   356.1  705.59  374.45705.5847   403.2  705.69   418.6  707.07     430  707.22
#Mann= 12 ,-1 , 0
       0     .12       0    64.5    .016       0   99.62     .06       0
  101.15     .12       0  152.49     .06       0  197.53     .12       0
  228.63     .06       0   241.3    .045       0   264.7     .08       0
  289.79    .016       0  326.37     .06       0  374.45    .016       0
#XS Ineff= 2 , 0
                          329.27          708.13
Permanent Ineff=
       F       F
Bank Sta=241.3,264.7
XS Rating Curve= 0 ,0
Exp/Cntr=0.3,0.1

Type RM Length L Ch R = 1 ,26881.2 ,123.7,122.2,120.6
XS GIS Cut Line= 2
     2295406.978      393055.893     2295373.558      392718.479
#Sta/Elev= 30
       0  729.28      12  726.84    39.9  723.62    43.9  722.75    51.9   720.5
   59.35719.1077    71.8  717.53    79.8  715.88    99.7   713.9   119.7  711.16
   127.6  709.43   139.6  705.71   143.6  704.69   147.6  704.08   155.6  703.86
  188.88704.2924  231.46704.0413   243.3  703.92  250.26  701.99   251.3  701.32
   255.3  700.52   259.3  700.42   263.3  700.48   267.3  701.91   271.2  703.63
   275.2  704.19   287.2  704.45   307.2  704.12  321.88704.9119   339.1  707.01
#Mann= 7 ,-1 , 0
       0     .08       0   59.35     .06       0  188.88     .12       0
  231.46     .06       0  250.26    .045       0   267.3     .06       0
  321.88    .016       0
Bank Sta=250.26,267.3
XS Rating Curve= 0 ,0
Exp/Cntr=0.3,0.1

Type RM Length L Ch R = 1 ,26759   ,112.2,119.1,126.4
XS GIS Cut Line= 3
     2295540.224      393017.959     2295485.537      392678.115
     2295462.099      392654.677
#Sta/Elev= 30
       0  720.81    23.7  718.53    43.5  718.23    47.5  717.89    63.2714.2367
    71.2  712.36    98.9  707.98   106.8  706.09   118.7  702.43   126.6  701.21
   134.5  700.94   193.5 701.058  213.92701.0544   229.5  701.13   233.4  700.74
   237.2  699.79   241.4   699.2   249.3  699.18   253.2  699.48   257.2  700.42
   261.1     701   280.9   701.2   300.7  702.61   324.4  703.23  336.78703.9152
   344.2  704.62   351.6  706.26   362.6  706.71   373.7  706.64   377.4  707.19
#Mann= 7 ,-1 , 0
       0     .08       0    63.2     .06       0   193.5     .12       0
  213.92     .06       0   237.2    .045       0   257.2     .06       0
  336.78    .016       0
#XS Ineff= 2 , 0
          157.12  703.27
Permanent Ineff=
       F       F
Bank Sta=237.2,257.2
XS Rating Curve= 0 ,0
Exp/Cntr=0.3,0.1

Type RM Length L Ch R = 1 ,26639.9 ,88.9,90,89.7
XS GIS Cut Line= 3
     2295588.401       393012.75     2295628.766      392688.531
     2295584.495      392601.292
#Sta/Elev= 30
       0  717.93    35.9  715.16    55.8  714.04    91.8 710.419    99.6  709.98
   107.6  708.99   127.5  705.05   139.4  701.72   143.4  700.84   147.4  700.32
   159.4   699.8   195.2  699.26   235.1  699.43   239.1   699.3     243  698.74
  249.04  697.33     255   696.1     259  696.37  262.52   697.3     267  698.93
   270.9  699.49   290.9  699.23   322.7  700.56   361.9  700.73   377.6  700.42
  387.85700.7431   397.2  701.29     405  702.39   408.9  702.58   424.6   702.4
#Mann= 5 ,-1 , 0
       0     .08       0    91.8     .06       0  249.04    .045       0
  262.52     .06       0  387.85    .016       0
#XS Ineff= 2 , 0
          191.91  701.63
Permanent Ineff=
       F       F
Bank Sta=249.04,262.52
XS Rating Curve= 0 ,0
Exp/Cntr=0.3,0.1

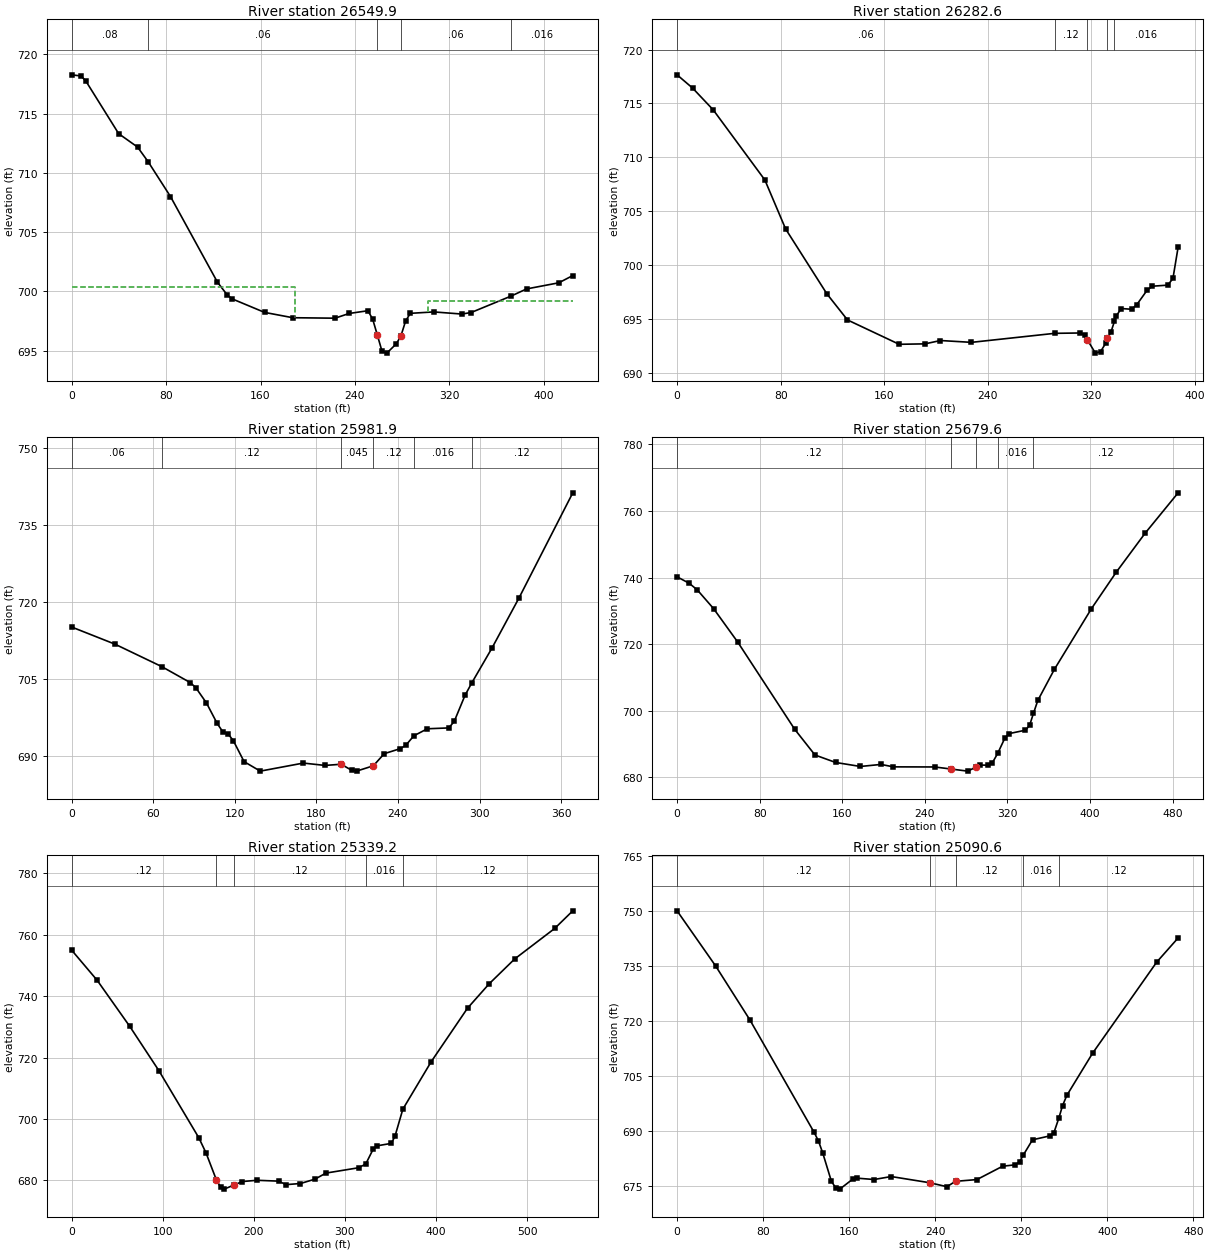
Type RM Length L Ch R = 1 ,26549.9 ,259.1,267.3,274.4
XS GIS Cut Line= 3
     2295673.037      393001.031     2295713.401      392676.813
     2295669.131      392589.573
#Sta/Elev= 30
       0  718.28       8  718.18      12  717.75    39.8  713.31    55.8  712.18
   64.76710.9423    83.7     708   123.5  700.77   131.5  699.73   135.5  699.38
   163.4  698.22   187.3  697.77   223.1  697.73   235.1  698.13     251  698.36
     255  697.66     259   696.3     263  694.92     267  694.78   274.9  695.55
   278.9  696.21   282.9  697.48   286.9  698.14   306.8  698.26   330.6  698.08
   338.5  698.21  372.45699.6031   385.4   700.2   412.8  700.72   424.6  701.33
#Mann= 5 ,-1 , 0
       0     .08       0   64.76     .06       0     259    .045       0
   278.9     .06       0  372.45    .016       0
#XS Ineff= 2 , 0
          189.35  700.33  302.31          699.22
Permanent Ineff=
       F       F
Bank Sta=259,278.9
XS Rating Curve= 0 ,0
Exp/Cntr=0.3,0.1

Type RM Length L Ch R = 1 ,26282.6 ,291,300.7,309.5
XS GIS Cut Line= 2
     2295824.078      393024.469     2295985.537      392672.906
#Sta/Elev= 30
       0  717.65      12  716.42    27.9   714.4    67.8  707.89    83.8  703.35
   115.7  697.32   131.6   694.9   171.5  692.64   191.4  692.68   203.4  692.99
   227.3  692.82  291.58693.6569   311.1  693.69   315.1   693.5  316.82  693.06
     323  691.82     327  691.96     331  692.74  332.22  693.18     335  693.76
   337.7694.7657     339  695.25     343  695.96     351  695.89     355  696.32
   362.9  697.65   366.9  698.03   378.9  698.13   382.9  698.75   386.9  701.66
#Mann= 5 ,-1 , 0
       0     .06       0  291.58     .12       0  316.82    .045       0
  332.22     .12       0   337.7    .016       0
Bank Sta=316.82,332.22
XS Rating Curve= 0 ,0
Exp/Cntr=0.3,0.1

Type RM Length L Ch R = 1 ,25981.9 ,295.3,302.3,306.4
XS GIS Cut Line= 2
     2295986.839      393093.479     2296257.672      392843.479
#Sta/Elev= 30
       0  715.06    31.7  711.74   66.18707.3625    87.2  704.24    91.2  703.28
    99.1  700.28     107  696.28     111  694.71   114.9  694.29   118.9  692.92
   126.8  688.84   138.7  686.99   170.4  688.56   186.3   688.1   198.2  688.33
   206.1  687.13     210  687.03   221.9  688.03   229.9  690.39   241.8  691.38
   245.7  692.01  251.72693.8773   261.6  695.24   277.4  695.41   281.4  696.68
   289.3  701.74  294.23704.1454   309.1  710.94     329  720.71   368.6  741.21
#Mann= 6 ,-1 , 0
       0     .06       0   66.18     .12       0   198.2    .045       0
   221.9     .12       0  251.72    .016       0  294.23     .12       0
Bank Sta=198.2,221.9
XS Rating Curve= 0 ,0
Exp/Cntr=0.3,0.1

Type RM Length L Ch R = 1 ,25679.6 ,329.1,340.4,344.2
XS GIS Cut Line= 3
     2296071.474      393344.781     2296179.547      393273.167
     2296477.724      393079.156
#Sta/Elev= 30
       0  740.21    11.8  738.27    19.6  736.28    35.4  730.66    58.9  720.57
   113.9  694.48   133.6  686.74   153.6   684.5   177.6   683.3   197.6  683.91
   209.6  683.18   249.6  683.15   265.6  682.52   281.5   681.9   289.5  683.08
   293.5  683.72   301.5  683.68   305.5  684.44  310.58687.2014   317.5  691.79
   321.5  693.15   337.5  694.19   341.5  695.62  345.25699.2481   349.5  703.13
   365.5  712.43   401.4  730.65   425.4  741.58   453.4  753.29   485.4  765.42
#Mann= 5 ,-1 , 0
       0     .12       0   265.6    .045       0   289.5     .12       0
  310.58    .016       0  345.25     .12       0
Bank Sta=265.6,289.5
XS Rating Curve= 0 ,0
Exp/Cntr=0.3,0.1

Type RM Length L Ch R = 1 ,25339.2 ,245.8,248.6,249.4
XS GIS Cut Line= 2
     2296133.727      393534.758     2296647.243      393337.097
#Sta/Elev= 30
       0  754.99    27.9  745.21    63.8  730.16    95.7  715.78   139.6   693.9
   147.5  688.96   158.7  680.32   163.5   677.8   167.5  677.19   178.7  678.61
   187.4  679.66   203.4  680.07   227.3  679.79   235.2  678.65   251.2  679.02
   267.2  680.45   279.1  682.41     315  684.15  322.85685.3636   330.9  690.14
   334.9  691.27   350.9  692.09   354.9  694.35  363.59703.2181   394.7  718.67
   434.6  736.11   458.5  744.09   486.4  752.14   530.3  762.07   550.2  767.82
#Mann= 5 ,-1 , 0
       0     .12       0   158.7    .045       0   178.7     .12       0
  322.85    .016       0  363.59     .12       0
Bank Sta=158.7,178.7
XS Rating Curve= 0 ,0
Exp/Cntr=0.3,0.1

Type RM Length L Ch R = 1 ,25090.6 ,298.1,297.6,292.5
XS GIS Cut Line= 2
     2296206.891      393726.292     2296653.506      393593.479
#Sta/Elev= 30
       0  749.96    35.8  734.96    67.7  720.24   127.4  689.61   131.4  687.29
   135.4  684.02   143.4  676.35   147.4  674.48   151.3  674.12   163.3  676.84
   167.3  677.11   183.2  676.74   199.1  677.55     235  675.86   250.9  674.78
   258.9  676.25   278.8  676.72   302.7  680.36   314.6  680.75   318.6  681.64
  322.03683.4493   330.5  687.56   346.5  688.62   350.4  689.51  354.92693.4122
   358.4  696.84   362.4  699.66   386.3  711.13     446  735.99   465.9  742.57
#Mann= 5 ,-1 , 0
       0     .12       0     235    .045       0   258.9     .12       0
  322.03    .016       0  354.92     .12       0
Bank Sta=235,258.9
XS Rating Curve= 0 ,0
Exp/Cntr=0.3,0.1

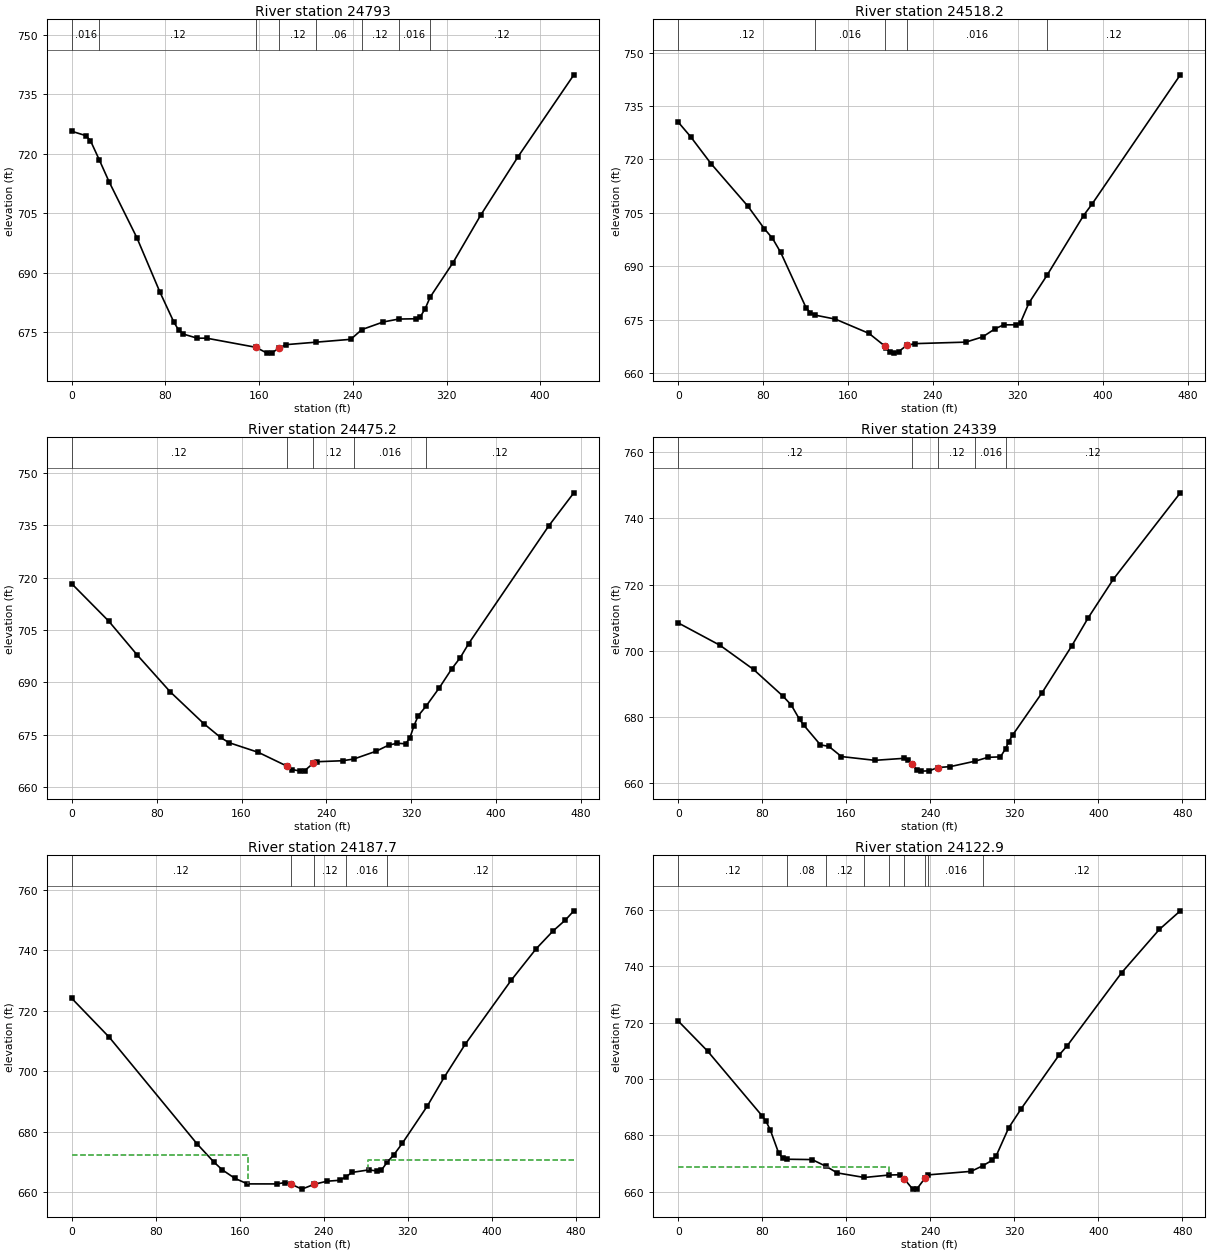
Type RM Length L Ch R = 1 ,24793   ,277.8,274.8,269.7
XS GIS Cut Line= 2
     2296331.891      393945.042     2296731.631      393790.094
#Sta/Elev= 30
       0  725.63    11.9  724.54    15.9   723.3   23.61718.3511    31.8  712.94
    55.6  698.79    75.4     685    87.3  677.44    91.3  675.49    95.3   674.5
   107.2  673.46   115.1  673.47   157.2  671.17   166.7   669.7   170.7  669.76
   177.2  670.99   182.6  671.83  208.48672.4588   238.2  673.18   247.7 675.636
     266  677.56  279.16678.2908   293.8  678.36   297.7  678.92   301.7  680.87
  306.01683.8166   325.5  692.49   349.3  704.55   381.1  719.24   428.7  739.86
#Mann= 8 ,-1 , 0
       0    .016       0   23.61     .12       0   157.2    .045       0
   177.2     .12       0  208.48     .06       0   247.7     .12       0
  279.16    .016       0  306.01     .12       0
Bank Sta=157.2,177.2
XS Rating Curve= 0 ,0
Exp/Cntr=0.3,0.1

Type RM Length L Ch R = 1 ,24518.2 ,42.8,43,42.8
XS GIS Cut Line= 3
     2296403.723      394179.308     2296500.077      394172.798
     2296828.202      393987.902
#Sta/Elev= 30
       0  730.49    11.6  726.43    30.9  718.83    65.7  706.86    81.1  700.57
    88.8  697.87    96.6  693.88   120.4  678.41   124.3  676.98  129.04676.2831
   148.1  675.16   179.8  671.15  194.48  667.65   195.7  666.94   199.6  666.03
   203.6  665.61   207.6  666.01   215.5  667.82   223.4  668.28     271   668.7
   286.9  670.17   298.8  672.48   306.7  673.55   318.6  673.57   322.6  674.19
   330.5  679.68  347.61687.4886     382  704.26     390  707.47   473.2  743.78
#Mann= 5 ,-1 , 0
       0     .12       0  129.04    .016       0  194.48    .045       0
   215.5    .016       0  347.61     .12       0
Bank Sta=194.48,215.5
XS Rating Curve= 0 ,0
Exp/Cntr=0.3,0.1

Type RM Length L Ch R = 1 ,24475.2 ,136.5,136.2,136.2
XS GIS Cut Line= 3
     2296424.556      394214.465      2296520.91      394207.954
     2296849.035      394023.058
#Sta/Elev= 30
       0  718.26    34.8  707.55    61.8  697.78    92.7  687.28   124.3  678.16
   140.2  674.17   148.1  672.68   175.9  669.88   202.5  665.98   207.6  664.96
   215.5   664.5   219.5  664.64   227.4   666.7   231.4   667.2   255.2  667.48
  265.74 667.966   286.9  670.22   298.8  671.98   306.7   672.5   314.6  672.34
   318.6  673.99   322.6  677.56   326.5  680.38  333.92683.1439   346.3  688.36
   358.2  693.88   366.2  697.08   374.1  701.11   449.4   734.8   473.2  744.35
#Mann= 5 ,-1 , 0
       0     .12       0   202.5    .045       0   227.4     .12       0
  265.74    .016       0  333.92     .12       0
Bank Sta=202.5,227.4
XS Rating Curve= 0 ,0
Exp/Cntr=0.3,0.1

Type RM Length L Ch R = 1 ,24339   ,150.9,151.3,150.8
XS GIS Cut Line= 2
     2296506.587      394369.413     2296923.254      394135.038
#Sta/Elev= 30
       0  708.38    39.8   701.6    71.7  694.29    99.6  686.25   107.6  683.54
   115.5  679.18   119.5  677.44   135.4  671.46   143.4  671.01   155.4  667.92
   187.2  666.78   215.1  667.39   219.1  666.91   222.8  665.55   227.1  663.89
   231.1  663.51     239  663.59     247   664.6     259  664.87  283.06666.5558
   294.8  667.68   306.8  667.83  311.84 670.345   314.7  672.44   318.7  674.56
   346.6  687.31   374.5   701.3   390.4  709.93   414.3   721.6   478.1  747.76
#Mann= 5 ,-1 , 0
       0     .12       0   222.8    .045       0     247     .12       0
  283.06    .016       0  311.84     .12       0
Bank Sta=222.8,247
XS Rating Curve= 0 ,0
Exp/Cntr=0.3,0.1

Type RM Length L Ch R = 1 ,24187.7 ,64.9,64.8,65.2
XS GIS Cut Line= 2
     2296588.618      394491.808     2297005.285      394257.433
#Sta/Elev= 30
       0  724.04    35.8  711.14   119.5  675.84   135.4  669.88   143.4  667.31
   155.4   664.5   167.3  662.68   195.2  662.67   203.2  663.14   208.4  662.66
   219.1  660.95   231.1  662.57     243  663.57     255  663.87  260.96665.0029
   266.9  666.48   282.8  667.31   290.8  666.94   294.8  667.22  300.56669.9368
   306.8  672.35   314.7  676.08   338.6  688.45   354.6  697.92   374.5  708.79
   418.3  729.97   442.2  740.44   458.1  746.26   470.1  749.97   478.1  752.99
#Mann= 5 ,-1 , 0
       0     .12       0   208.4    .045       0   231.1     .12       0
  260.96    .016       0  300.56     .12       0
#XS Ineff= 2 , 0
          167.52  672.12  282.41          670.46
Permanent Ineff=
       F       F
Bank Sta=208.4,231.1
XS Rating Curve= 0 ,0
Exp/Cntr=0.3,0.1

Type RM Length L Ch R = 1 ,24122.9 ,31,30.9,31
XS GIS Cut Line= 2
     2296628.202      394540.767     2297044.868      394306.392
#Sta/Elev= 30
       0  720.58    27.9  709.93    79.7  686.99    83.7  684.92    87.6  681.96
    95.6  673.73    99.6  671.84   103.4 671.517   127.5  671.39  141.02 668.939
   151.4  666.66  177.27665.0315  200.46665.8987   211.1  666.01   215.1  664.59
   223.1  660.97   227.1   660.9     235   664.8  238.22665.9672   278.9  667.21
  290.16669.2224   298.8  671.12   302.8  672.74   314.7  682.68   326.7  689.51
   362.5  708.43   370.5  711.85   422.3  737.77   458.1  753.09   478.1  759.71
#Mann= 9 ,-1 , 0
       0     .12       0   103.4     .08       0  141.02     .12       0
  177.27     .08       0  200.46     .12       0   215.1    .045       0
     235     .12       0  238.22    .016       0  290.16     .12       0
#XS Ineff= 2 , 0
          200.26  668.93
Permanent Ineff=
       F       F
Bank Sta=215.1,235
XS Rating Curve= 0 ,0
Exp/Cntr=0.3,0.1

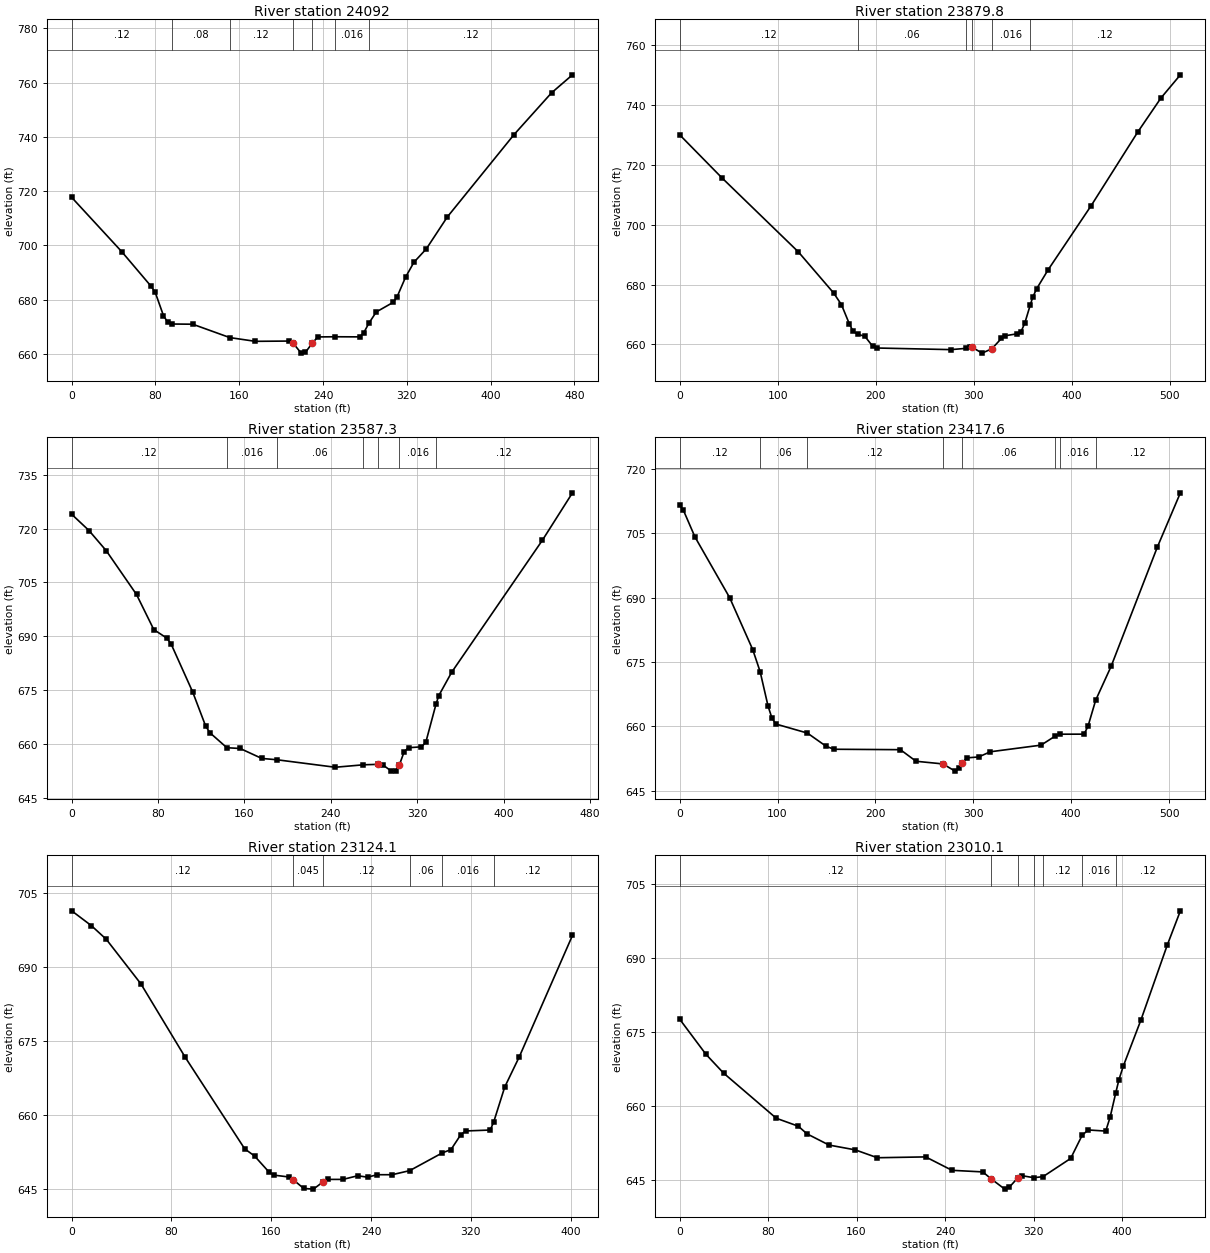
Type RM Length L Ch R = 1 ,24092   ,211.7,212.2,211.3
XS GIS Cut Line= 2
     2296648.514      394563.683     2297065.181      394329.308
#Sta/Elev= 30
       0  717.65    47.8  697.64    75.7  684.94    79.7  682.69    87.6  674.08
    91.6  671.68    95.9 670.983   115.5  670.91  150.96665.9751   175.3   664.6
   207.2   664.7   211.1  664.06   219.1  660.25   223.1   660.5  229.78  663.98
     235  666.22  251.63666.2826   274.9  666.24   278.9  667.81  283.73671.2738
   290.8  675.43   306.8  678.94   310.7  681.05   318.7   688.2   326.7  693.73
   338.6   698.7   358.6  710.44   422.3   740.8   458.1  756.19   478.1  762.84
#Mann= 7 ,-1 , 0
       0     .12       0    95.9     .08       0  150.96     .12       0
   211.1    .045       0  229.78     .08       0  251.63    .016       0
  283.73     .12       0
Bank Sta=211.1,229.78
XS Rating Curve= 0 ,0
Exp/Cntr=0.3,0.1

Type RM Length L Ch R = 1 ,23879.8 ,294.5,292.5,289.6
XS GIS Cut Line= 4
     2296671.917       394720.34      2296793.12      394723.567
     2296956.417      394631.712     2297132.114      394531.379
#Sta/Elev= 30
       0     730      43  715.67   121.2  690.88   157.1   677.2   165.1  673.29
   173.1  666.93     177  664.35  182.15663.3738     189  662.73     197  659.38
     201  658.82   276.7  658.28  292.12658.6967   296.6  659.27   298.6  659.03
   308.6  657.11   318.6  658.57   328.4  662.05   332.4  662.92   344.3  663.56
   348.3  664.24   352.2  667.16  357.64673.0632   360.2   675.7   364.2  678.56
     376  684.94   419.7  706.24   467.3  730.85   491.1  742.28   510.9     750
#Mann= 6 ,-1 , 0
       0     .12       0  182.15     .06       0  292.12     .12       0
   298.6    .045       0   318.6    .016       0  357.64     .12       0
Bank Sta=298.6,318.6
XS Rating Curve= 0 ,0
Exp/Cntr=0.3,0.1

Type RM Length L Ch R = 1 ,23587.3 ,169.4,169.7,169.4
XS GIS Cut Line= 3
     2296868.876      395042.048     2297156.114      394838.691
     2297239.772      394764.537
#Sta/Elev= 30
       0  724.01      16  719.49      32  713.86      60  701.66      76  691.88
      88   689.5      92  687.89     112  674.49     124     665     128   663.1
  143.69658.9382     156  658.72     176  655.95  189.98655.5807     244  653.49
  270.19654.1764   283.5   654.3     288  654.17     296  652.41     300  652.49
   303.5   654.2   307.9  657.87   311.9  658.94   323.9  659.18   327.9  660.46
  337.35671.0885   339.9  673.46   351.9     680   435.8  716.76   463.7     730
#Mann= 7 ,-1 , 0
       0     .12       0  143.69    .016       0  189.98     .06       0
  270.19     .12       0   283.5    .045       0   303.5    .016       0
  337.35     .12       0
Bank Sta=283.5,303.5
XS Rating Curve= 0 ,0
Exp/Cntr=0.3,0.1

Type RM Length L Ch R = 1 ,23417.6 ,322,293.6,261.8
XS GIS Cut Line= 4
     2296920.422      395091.572     2297053.631      395102.363
     2297281.439      394947.357      2297307.25       394848.33
#Sta/Elev= 30
       0  711.58     3.9  710.36    15.7  704.14    51.1  690.01    74.7  677.88
   82.24672.7516    90.4  664.66    94.3  661.94    98.3  660.54  130.55658.4285
   149.6  655.36   157.6  654.66   225.5  654.56   241.5  651.86   268.9  651.24
   281.4  649.56   285.4  650.21   288.9  651.49   293.4  652.65   305.4  652.86
   317.3  654.07   369.2  655.62  383.65657.7314  388.19658.1693   413.1  658.18
   417.1  659.99  424.99666.0987   440.7  673.96   487.9  701.75   511.5  714.44
#Mann= 8 ,-1 , 0
       0     .12       0   82.24     .06       0  130.55     .12       0
   268.9    .045       0   288.9     .06       0  383.65     .12       0
  388.19    .016       0  424.99     .12       0
Bank Sta=268.9,288.9
XS Rating Curve= 0 ,0
Exp/Cntr=0.3,0.1

Type RM Length L Ch R = 1 ,23124.1 ,118,114,108.3
XS GIS Cut Line= 4
     2297324.501       395266.87     2297387.375      395134.456
     2297347.439      394949.681     2297347.375      394883.792
#Sta/Elev= 30
       0  701.43    15.8  698.42    27.7  695.67    55.5  686.63    91.1  671.73
   138.7  653.22   146.6  651.77   158.4  648.46   162.3  647.89   174.2  647.52
   177.6  646.97     186   645.2   193.8  645.06   201.7  646.56   205.7  647.03
   217.5  647.03   229.3  647.77   237.2  647.48     245  647.98   256.9  647.98
  270.99648.8049  297.27652.4183   304.1  653.07     312   656.1   315.9  656.84
   335.6  657.03  338.44 658.734   347.2  665.75   358.9  671.88   401.5  696.45
#Mann= 6 ,-1 , 0
       0     .12       0   177.6    .045       0   201.7     .12       0
  270.99     .06       0  297.27    .016       0  338.44     .12       0
Bank Sta=177.6,201.7
XS Rating Curve= 0 ,0
Exp/Cntr=0.3,0.1

Type RM Length L Ch R = 1 ,23010.1 ,209.3,231.8,253.8
XS GIS Cut Line= 3
     2297590.397      395294.789     2297428.087      394940.928
     2297425.831      394877.426
#Sta/Elev= 30
       0  677.65    23.8  670.52    39.7  666.72    87.4  657.56   107.3  655.95
   115.2   654.4   135.1  652.13   158.9  651.15   178.8  649.56   222.5  649.73
   246.3  647.01   274.1  646.69     282  645.23     294   643.2   297.9  643.53
   305.9  645.52   309.9  645.91  320.24645.5173  328.61645.7281   353.6  649.42
  363.96654.1049   369.4  655.19   385.3  654.96   389.3   657.8  394.25662.5942
   397.2  665.34   401.2  668.13   417.1  677.46   440.9  692.62   452.8  699.59
#Mann= 7 ,-1 , 0
       0     .12       0     282    .045       0   305.9     .12       0
  320.24     .06       0  328.61     .12       0  363.96    .016       0
  394.25     .12       0
Bank Sta=282,305.9
XS Rating Curve= 0 ,0
Exp/Cntr=0.3,0.1

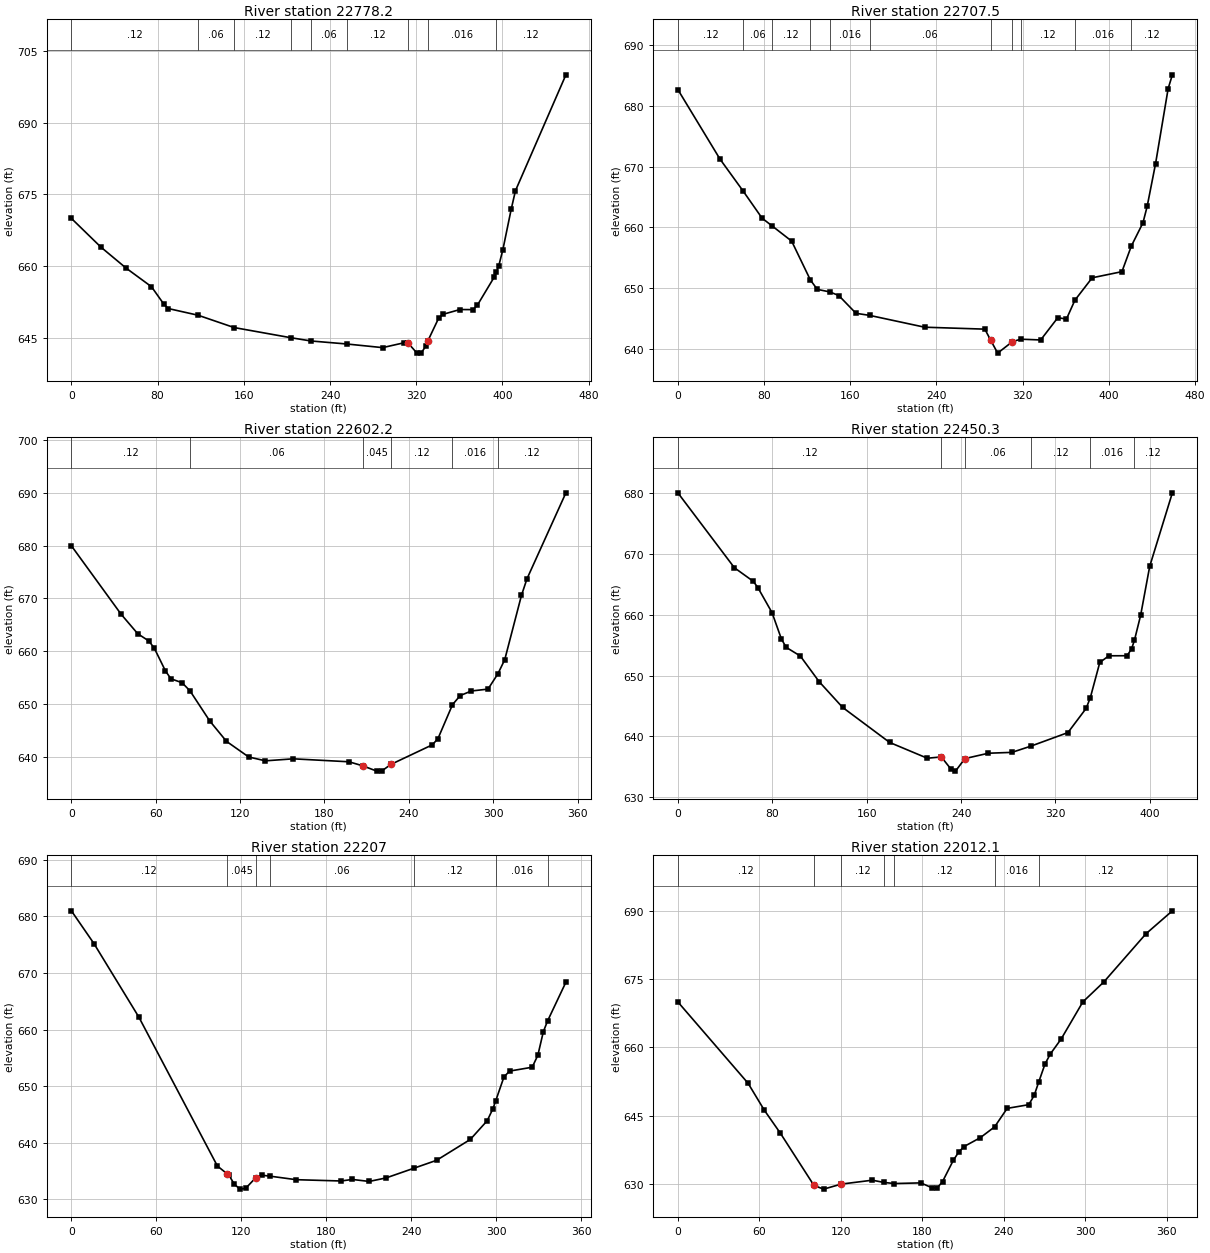
Type RM Length L Ch R = 1 ,22778.2 ,71.1,70.7,71
XS GIS Cut Line= 4
     2297629.179      395237.602     2297574.344      395138.307
     2297705.292      394887.359     2297696.114      394825.664
#Sta/Elev= 30
       0     670    27.4     664    50.8  659.61    74.3  655.73      86  652.02
      90  651.16  117.62649.7652     151647.1937  203.91645.0593  222.38644.3884
  255.46643.7601   288.8     643   308.8  644.02   312.8  643.87   320.7  641.85
   324.7  641.91   328.7  643.24  330.55  644.29   340.7   649.1   344.7  649.95
   360.6  650.96   372.6  650.94   376.6  651.81   392.5  657.78  394.39658.8337
   396.5  660.01   400.4  663.46   408.2  671.98   412.1  675.79   458.9     700
#Mann= 9 ,-1 , 0
       0     .12       0  117.62     .06       0     151     .12       0
  203.91    .016       0  222.38     .06       0  255.46     .12       0
   312.8    .045       0  330.55    .016       0  394.39     .12       0
Bank Sta=312.8,330.55
XS Rating Curve= 0 ,0
Exp/Cntr=0.3,0.1

Type RM Length L Ch R = 1 ,22707.5 ,119.8,105.4,89
XS GIS Cut Line= 4
     2297701.005      395251.829     2297646.171      395152.534
     2297777.118      394901.587     2297767.941      394839.891
#Sta/Elev= 30
       0  682.67    39.1  671.22   60.57665.9565    78.2  661.48   87.47660.2126
   105.6  657.71     123 651.302   129.4  649.76  140.98649.3433   149.3  648.75
   165.3  645.82  177.89645.4793     229  643.53   284.9  643.21   290.3  641.38
   296.8  639.26   310.3  641.13  318.07641.5565   336.7  641.43   352.6   645.1
   360.6  644.87  368.46647.9798   384.5  651.67   412.1  652.68  420.83656.9001
   431.6  660.72   435.5  663.42   443.3  670.46     455  682.84   458.9   685.1
#Mann= 11 ,-1 , 0
       0     .12       0   60.57     .06       0   87.47     .12       0
     123     .06       0  140.98    .016       0  177.89     .06       0
   290.3    .045       0   310.3     .06       0  318.07     .12       0
  368.46    .016       0  420.83     .12       0
Bank Sta=290.3,310.3
XS Rating Curve= 0 ,0
Exp/Cntr=0.3,0.1

Type RM Length L Ch R = 1 ,22602.2 ,145.5,151.8,158
XS GIS Cut Line= 3
     2297847.346       395171.77     2297843.299      395081.354
     2297812.114       394822.01
#Sta/Elev= 30
       0  679.97    35.4     667    47.2  663.32    55.1  661.95      59  660.57
    66.9  656.28    70.8  654.79    78.7  654.05   84.36652.5064    98.4  646.81
   110.3  642.95   126.1  639.99     138  639.26   157.8  639.64   197.4  639.08
   207.3  638.31   217.2  637.31   221.1  637.41   227.3  638.59   256.7  642.29
   260.7  643.46  271.04649.8881   276.5  651.61   284.4  652.48   296.3  652.84
  303.37655.7512   308.2  658.41   320.1  670.59     324  673.71   351.7     690
#Mann= 6 ,-1 , 0
       0     .12       0   84.36     .06       0   207.3    .045       0
   227.3     .12       0  271.04    .016       0  303.37     .12       0
Bank Sta=207.3,227.3
XS Rating Curve= 0 ,0
Exp/Cntr=0.3,0.1

Type RM Length L Ch R = 1 ,22450.3 ,257.7,243.3,228.8
XS GIS Cut Line= 4
     2297912.114      395187.973     2297964.168       395084.59
     2297990.678      394879.102      2297945.66      394794.082
#Sta/Elev= 30
       0     680    47.9   667.7    63.9  665.47    67.8  664.44    79.8  660.33
    87.8  655.98    91.8  654.63   103.8   653.2   119.7     649   139.6  644.77
   179.5  639.01   211.4  636.42   223.3  636.63   231.3  634.67   235.3   634.3
   243.3  636.36   263.2  637.24   283.1  637.38  299.02638.3919   330.6  640.63
     346   644.6  349.55646.3477   357.6  652.15   365.3  653.24   380.7  653.25
   384.5  654.37  386.91655.7542   392.2  659.88   399.9  667.93   419.1     680
#Mann= 6 ,-1 , 0
       0     .12       0   223.3    .045       0   243.3     .06       0
  299.02     .12       0  349.55    .016       0  386.91     .12       0
Bank Sta=223.3,243.3
XS Rating Curve= 0 ,0
Exp/Cntr=0.3,0.1

Type RM Length L Ch R = 1 ,22207   ,191.1,194.9,198.4
XS GIS Cut Line= 3
     2298260.898      395060.496     2298240.378      394992.114
     2298119.861      394741.816
#Sta/Elev= 30
       0     681    15.9  675.22    47.6  662.22   103.1  635.87   110.1  634.46
   111.1  634.31     115  632.67     119  631.78     123  631.91   130.1  633.77
   134.9  634.23  140.46 634.066   158.7  633.45   190.4  633.22   198.4  633.49
   210.3  633.14   222.2  633.76  241.87 635.477   257.9  636.88   281.7  640.57
   293.6  643.87   297.6  645.96  299.49647.2925   305.5  651.65   309.5  652.66
   325.4  653.34   329.4  655.46   333.3  659.65  336.31661.5538   349.2  668.38
#Mann= 7 ,-1 , 0
       0     .12       0   110.1    .045       0   130.1     .12       0
  140.46     .06       0  241.87     .12       0  299.49    .016       0
  336.31     .12       0
Bank Sta=110.1,130.1
XS Rating Curve= 0 ,0
Exp/Cntr=0.3,0.1

Type RM Length L Ch R = 1 ,22012.1 ,192.1,192.3,191.6
XS GIS Cut Line= 3
     2298420.696      394956.537     2298331.644      394672.066
      2298279.43      394631.854
#Sta/Elev= 30
       0     670    51.7  652.14    63.6  646.25    75.5  641.16   100.2   629.7
   107.3   628.9   120.2     630   143.1  630.86  151.88630.3616  159.39630.1276
   178.8  630.27   186.8  629.23   190.8  629.13   194.8  630.54   202.7  635.19
   206.7  637.02   210.6  638.24   222.6  640.19  233.16642.5679   242.4  646.63
   258.3  647.44   262.3  649.48   265.6652.3923   270.3  656.41   274.2  658.58
   282.2  661.89   298.1     670   313.6   674.4   344.6  684.97     364     690
#Mann= 7 ,-1 , 0
       0     .12       0   100.2    .045       0   120.2     .12       0
  151.88     .06       0  159.39     .12       0  233.16    .016       0
   265.6     .12       0
Bank Sta=100.2,120.2
XS Rating Curve= 0 ,0
Exp/Cntr=0.3,0.1