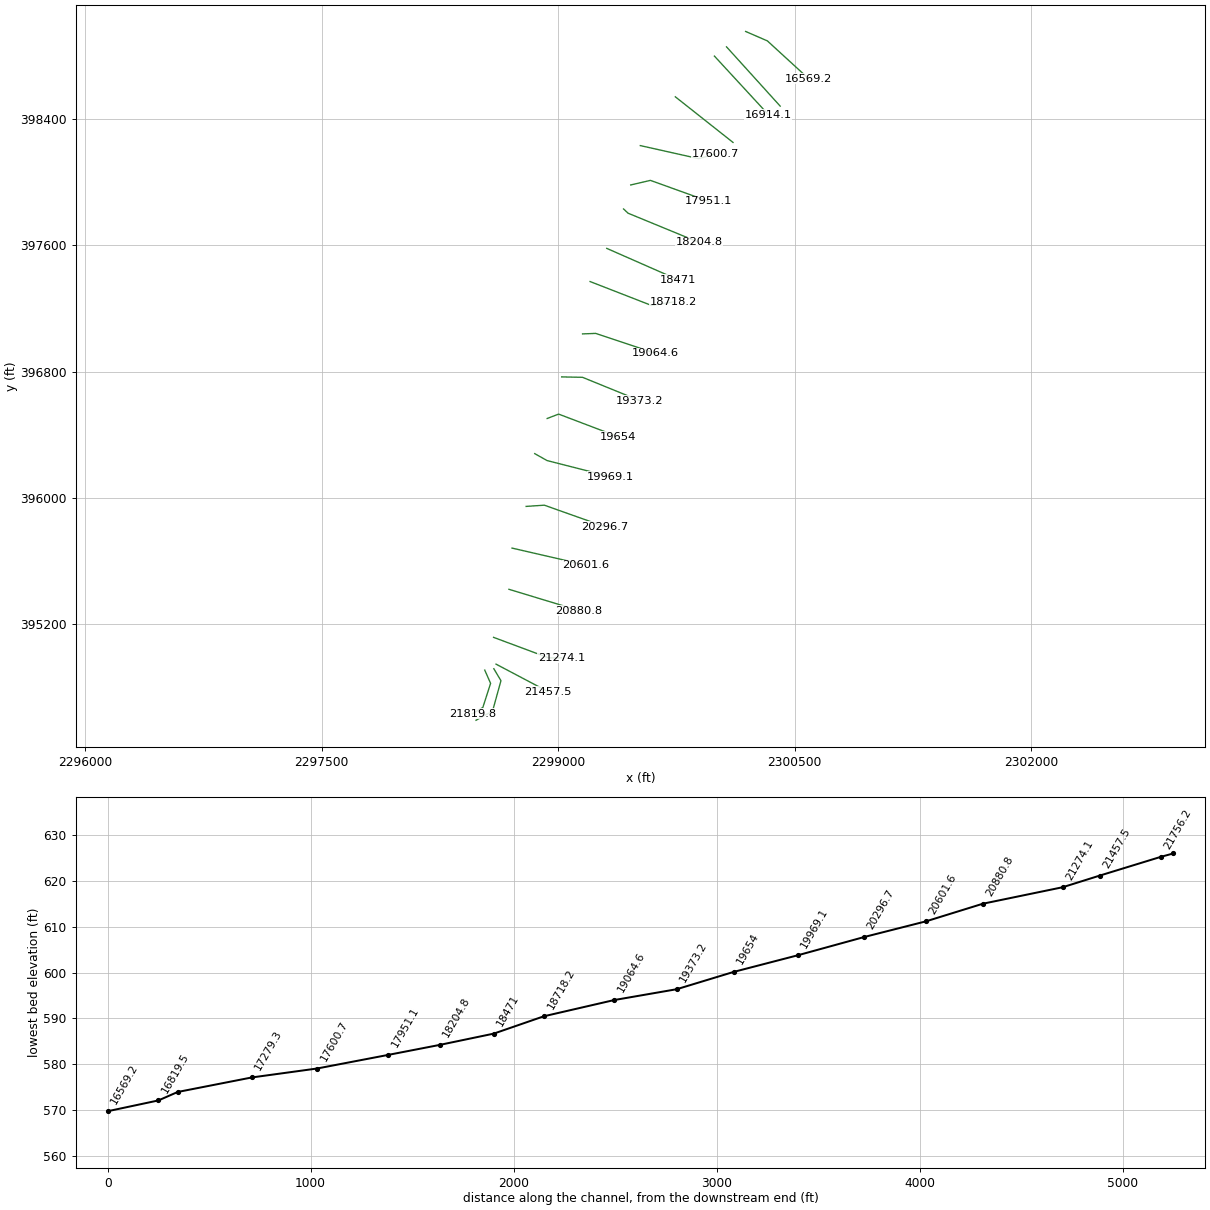
HEC-RAS study LONGHOLLOW.prj: LONGHOLLOW

--- LONGHOLLOW.g01 (geometry) --- (continued)

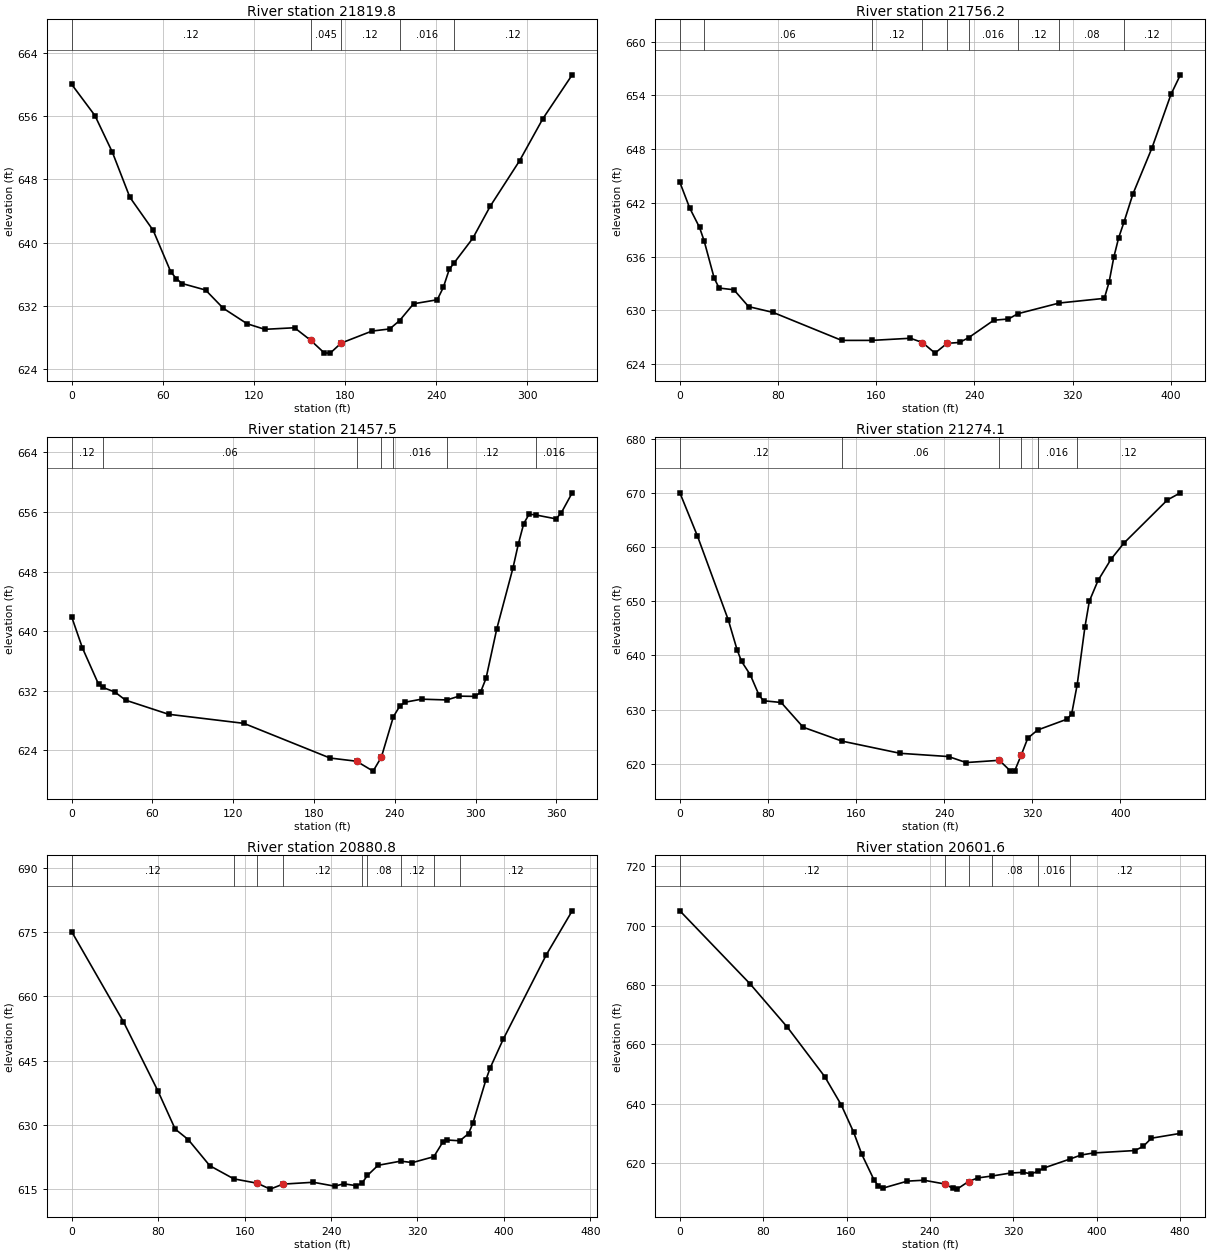
Type RM Length L Ch R = 1 ,21819.8 ,61.8,63.6,65.3
XS GIS Cut Line= 4
     2298533.928      394906.725      2298571.04      394822.538
     2298521.804      394669.696     2298455.794      394629.819
#Sta/Elev= 30
       0     660    15.3  656.06    26.8  651.42    38.3  645.73    53.7  641.53
    65.2  636.32      69  635.41    72.8  634.81    88.2  633.99    99.8  631.69
   115.5  629.73   127.2  629.02   146.8  629.22   157.5  627.62   166.4  626.03
   170.3  626.01   177.5  627.28   197.8   628.8   209.5  629.07     216630.1266
   225.2  632.25   240.8  632.76   244.8  634.32   248.7   636.6  251.69637.3666
   264.2  640.53   275.7  644.59     295  650.33   310.4  655.67   329.7  661.21
#Mann= 5 ,-1 , 0
       0     .12       0   157.5    .045       0   177.5     .12       0
     216    .016       0  251.69     .12       0
Bank Sta=157.5,177.5
XS Rating Curve= 0 ,0
Exp/Cntr=0.3,0.1

Type RM Length L Ch R = 1 ,21756.2 ,264.1,298.7,331.9
XS GIS Cut Line= 4
     2298591.616      394915.155       2298636.7       394839.64
     2298583.534      394646.963     2298478.581      394588.586
#Sta/Elev= 30
       0  644.29       8  641.43      16  639.27   19.75  637.77      28  633.59
      32   632.5      44  632.31      56  630.43      76  629.78   131.9  626.66
  156.58626.6617   187.9   626.9   197.7  626.42   207.9  625.24   217.7  626.33
   227.9  626.43  235.36626.9681   255.8  628.91   267.8  629.05  275.45629.6385
  309.15  630.83   345.9  631.35   349.8  633.17   353.7  635.98   357.6  638.11
  361.88639.8381   369.2  642.99   384.7  648.12   400.2   654.1   407.9  656.29
#Mann= 9 ,-1 , 0
       0     .12       0   19.75     .06       0  156.58     .12       0
   197.7    .045       0   217.7     .12       0  235.36    .016       0
  275.45     .12       0  309.15     .08       0  361.88     .12       0
Bank Sta=197.7,217.7
XS Rating Curve= 0 ,0
Exp/Cntr=0.3,0.1

Type RM Length L Ch R = 1 ,21457.5 ,180.4,183.4,186.8
XS GIS Cut Line= 2
     2298605.534      394944.489      2298934.31      394770.878
#Sta/Elev= 30
       0   641.9       8  637.72      20  632.84   22.89632.4426      32  631.82
      40  630.72      72  628.82   127.9   627.6   191.9  622.94   211.6  622.51
   223.9  621.18  230.04  623.06  238.99628.4995   243.9  629.97   247.9  630.45
   259.9  630.85  278.69630.7451   287.8  631.26   299.8  631.22   303.8  631.82
   307.8  633.66   315.8  640.32   327.8  648.48   331.8  651.71   335.8  654.45
   339.8  655.71  344.63655.6111   359.8  655.08   363.8  655.93   371.8  658.58
#Mann= 7 ,-1 , 0
       0     .12       0   22.89     .06       0   211.6    .045       0
  230.04     .06       0  238.99    .016       0  278.69     .12       0
  344.63    .016       0
Bank Sta=211.6,230.04
XS Rating Curve= 0 ,0
Exp/Cntr=0.3,0.1

Type RM Length L Ch R = 1 ,21274.1 ,388.9,393.3,394.9
XS GIS Cut Line= 3
      2298589.91      395114.332      2298938.47      394984.537
     2299021.164      394984.537
#Sta/Elev= 30
       0     670      16     662      44  646.52      52     641      56  638.89
      64  636.39      72   632.6      76  631.62      92   631.3     112  626.73
  147.05624.1789     200  621.92     244  621.32     260  620.21   290.2  620.63
     300  618.69     304  618.63   310.2  621.68     316  624.72  324.92 626.219
   351.9  628.24   355.9  629.24  360.88634.5978   367.9  645.25   371.9     650
   379.8  653.82   391.6  657.75   403.4  660.74   442.8  668.69   454.6     670
#Mann= 6 ,-1 , 0
       0     .12       0  147.05     .06       0   290.2    .045       0
   310.2     .06       0  324.92    .016       0  360.88     .12       0
Bank Sta=290.2,310.2
XS Rating Curve= 0 ,0
Exp/Cntr=0.3,0.1

Type RM Length L Ch R = 1 ,20880.8 ,277.9,279.2,280.2
XS GIS Cut Line= 2
     2298687.468      395419.044      2299130.68      395284.537
#Sta/Elev= 30
       0  675.13    47.9   654.1    79.9   637.9    95.8  629.04   107.8  626.61
   127.8   620.5  149.99617.4294   171.7  616.41   183.7  615.03   195.6   616.2
   223.6  616.63   243.6  615.71   251.6  616.28   263.5  615.83   268.6 616.411
  273.74 618.234   283.5  620.59  304.44621.5611   315.4  621.23  335.13622.5989
   343.4  625.99   347.4   626.5   359.2626.3115   367.3     628   371.3  630.43
   383.3  640.51   387.3  643.33   399.3  649.99   439.2  669.72   463.2     680
#Mann= 9 ,-1 , 0
       0     .12       0  149.99     .06       0   171.7    .045       0
   195.6     .12       0   268.6     .06       0  273.74     .08       0
  304.44     .12       0  335.13    .016       0   359.2     .12       0
Bank Sta=171.7,195.6
XS Rating Curve= 0 ,0
Exp/Cntr=0.3,0.1

Type RM Length L Ch R = 1 ,20601.6 ,307.1,304.9,301.4
XS GIS Cut Line= 2
     2298707.144      395680.383     2299175.379      395572.537
#Sta/Elev= 30
       0  705.03    67.5  680.36   103.2  665.79     139  649.16   154.9  639.61
   166.8   630.4   174.7  622.88   186.6  614.14   190.6  612.28   194.6   611.5
   218.4   613.9   234.3   614.2   254.2  612.94   262.1  611.45   266.1   611.2
   277.1  613.76   285.9  614.97  299.51615.6169   317.7  616.64   329.6  616.86
   337.5  616.35  344.01617.2759   349.4  618.31  374.19621.3083   385.2   622.7
   397.1  623.39   436.8  624.21   444.8  625.61   452.7  628.37   480.5     630
#Mann= 6 ,-1 , 0
       0     .12       0   254.2    .045       0   277.1     .12       0
  299.51     .08       0  344.01    .016       0  374.19     .12       0
Bank Sta=254.2,277.1
XS Rating Curve= 0 ,0
Exp/Cntr=0.3,0.1

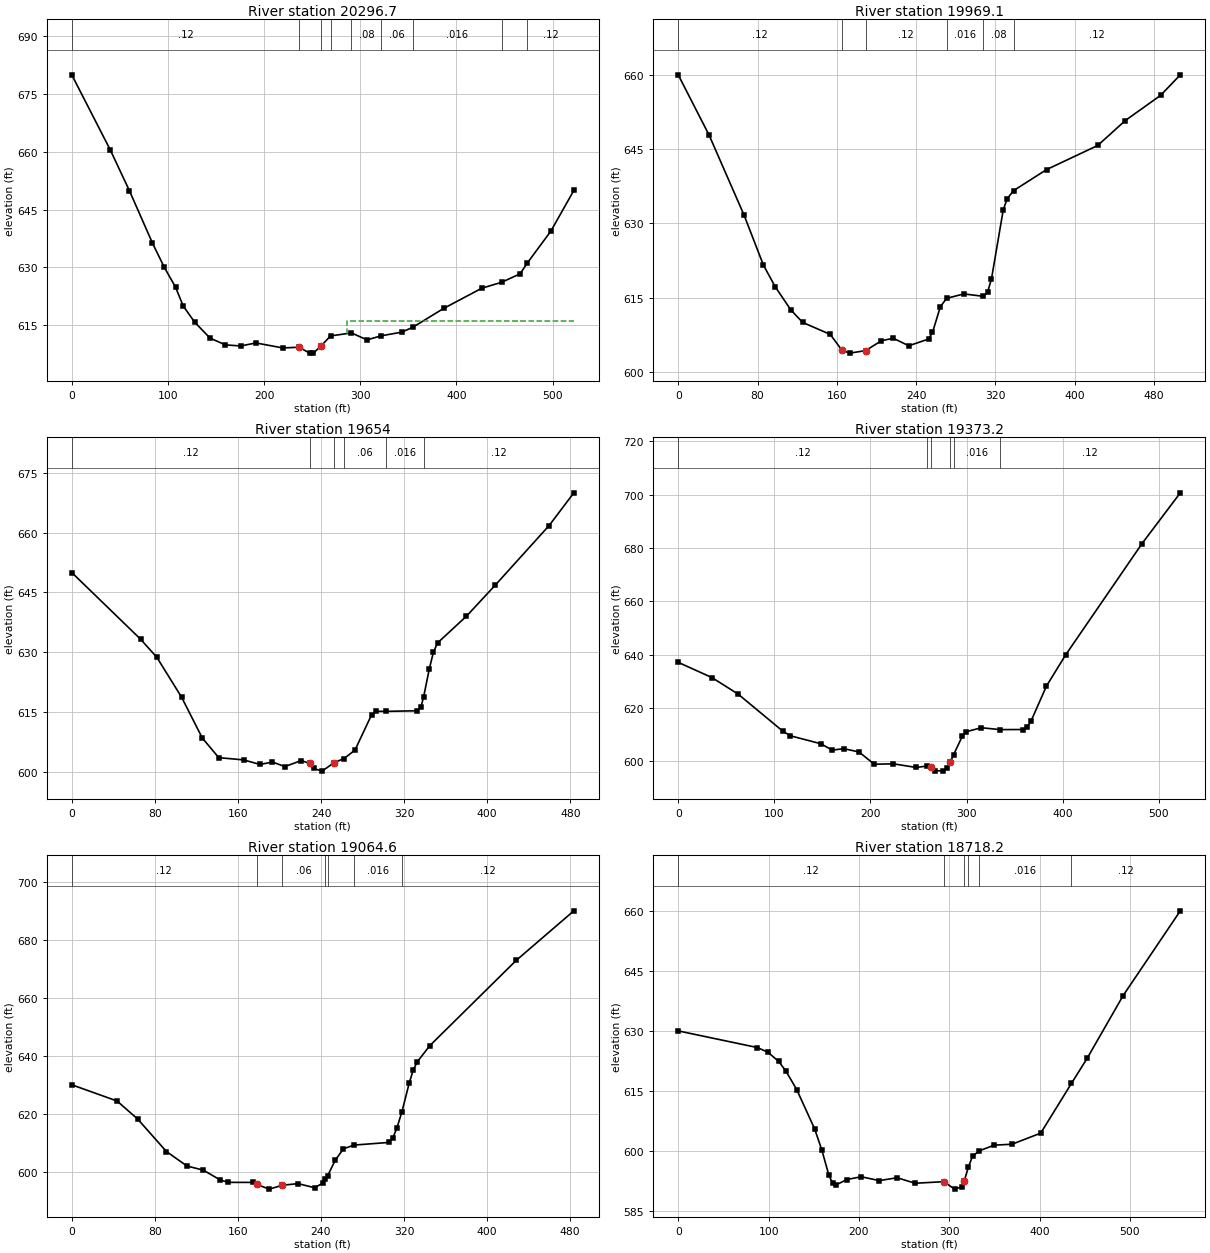
Type RM Length L Ch R = 1 ,20296.7 ,323.8,327.6,328.8
XS GIS Cut Line= 3
     2298796.243      395944.666     2298911.844      395952.537
     2299294.623      395816.537
#Sta/Elev= 30
       0     680      40  660.53    59.9  649.95    83.9  636.34    95.9  630.19
   107.9  624.89   115.9     620   127.8   615.8   143.8  611.67   159.7  609.91
   175.6  609.63   191.5  610.41   219.4  609.12   236.4   609.3   247.3  607.77
   251.3  607.78   259.2  609.63  269.14612.2382  290.88613.0117     307  611.21
  322.02612.2808   342.9   613.2  354.48614.4556   386.7  619.37   426.5  624.63
  447.01626.1573   466.3  628.36  473.33631.0332   498.2  639.43   522.1     650
#Mann= 9 ,-1 , 0
       0     .12       0   236.4    .045       0   259.2     .12       0
  269.14    .016       0  290.88     .08       0  322.02     .06       0
  354.48    .016       0  447.01     .06       0  473.33     .12       0
#XS Ineff= 2 , 0
                          286.52          616.12
Permanent Ineff=
       F       F
Bank Sta=236.4,259.2
XS Rating Curve= 0 ,0
Exp/Cntr=0.3,0.1

Type RM Length L Ch R = 1 ,19969.1 ,317.3,315.1,310.4
XS GIS Cut Line= 3
     2298850.952      396279.375     2298929.234      396235.416
     2299333.044      396132.537
#Sta/Elev= 30
       0  659.99    31.2  647.79    66.4  631.66    85.9  621.58    97.7  617.23
   113.6  612.51   125.5  609.98   153.3  607.57   165.2  604.36   173.1  603.78
     189  604.29   204.9  606.27   216.8  606.79   232.6  605.27   252.5  606.62
   256.5  607.95   264.4  613.14   270.7 614.848   288.2  615.74  307.89615.2526
     312  616.05     316  618.77   327.9  632.75   331.9  634.98  338.23636.5974
   371.6  640.86   423.2  645.73   450.9  650.75   486.6  655.85   506.5     660
#Mann= 6 ,-1 , 0
       0     .12       0   165.2    .045       0     189     .12       0
   270.7    .016       0  307.89     .08       0  338.23     .12       0
Bank Sta=165.2,189
XS Rating Curve= 0 ,0
Exp/Cntr=0.3,0.1

Type RM Length L Ch R = 1 ,19654   ,280.8,280.8,279.1
XS GIS Cut Line= 3
     2298929.799      396502.223     2299002.551        396530.1
     2299381.585      396386.008
#Sta/Elev= 30
       0     650    66.2  633.28    81.9  628.72   105.7  618.73   125.6   608.5
   141.5  603.54   165.4  602.98   181.3  601.83   193.2  602.44   205.1  601.31
     221  602.81     229  602.09     233  600.82   240.9  600.16   252.8  602.31
  262.23603.3272   272.7  605.45   288.6  614.26   292.6  615.16  303.01615.1686
   332.3   615.3   336.3  616.35  338.74618.7656   344.3  625.88   348.2  630.01
   352.2  632.34     380  639.04   407.9  646.88   459.6  661.79   483.4     670
#Mann= 6 ,-1 , 0
       0     .12       0     229    .045       0   252.8     .12       0
  262.23     .06       0  303.01    .016       0  338.74     .12       0
Bank Sta=229,252.8
XS Rating Curve= 0 ,0
Exp/Cntr=0.3,0.1

Type RM Length L Ch R = 1 ,19373.2 ,306.3,308.6,309.8
XS GIS Cut Line= 3
     2299021.743      396766.012     2299154.112      396763.328
     2299515.365      396616.152
#Sta/Elev= 30
       0  637.13      35  631.44    62.3  625.24     109   611.3   116.8  609.61
   148.3  606.65   160.3  604.24   172.2   604.8   188.1  603.56     204  598.97
     224  599.12   247.8  597.74  258.62598.2874     263  597.78   267.7   596.6
   275.7  596.38   279.7  597.38     283  599.65  286.63602.5825   295.6  609.43
   299.6  611.13   315.5  612.64  334.83611.9357   359.3  611.97   363.3  612.91
   367.2  615.17   383.2  628.25   403.1  639.88   482.7  681.65   522.5  700.64
#Mann= 6 ,-1 , 0
       0     .12       0  258.62     .06       0     263    .045       0
     283     .06       0  286.63    .016       0  334.83     .12       0
Bank Sta=263,283
XS Rating Curve= 0 ,0
Exp/Cntr=0.3,0.1

Type RM Length L Ch R = 1 ,19064.6 ,346,346.4,343.6
XS GIS Cut Line= 3
     2299154.241      397038.664     2299237.407       397041.83
     2299617.379      396915.273
#Sta/Elev= 30
       0     630    43.6  624.41    63.4  618.21    91.2  606.98     111  601.98
   126.8  600.55   142.7  597.24   150.6  596.34   174.4  596.33   178.4  595.61
   190.3  594.01   202.7  595.34     218  595.91   233.9   594.5   241.8  596.07
  244.35597.3578  246.48598.5915   253.7   603.9   261.7  607.92  271.94609.2019
   305.3  610.11   309.2  611.56   313.2  615.07  318.09 620.694   325.1  630.62
   329.1  635.24     333  637.98   344.9  643.48   428.2  672.91   483.7     690
#Mann= 7 ,-1 , 0
       0     .12       0   178.4    .045       0   202.7     .06       0
  244.35     .12       0  246.48     .06       0  271.94    .016       0
  318.09     .12       0
Bank Sta=178.4,202.7
XS Rating Curve= 0 ,0
Exp/Cntr=0.3,0.1

Type RM Length L Ch R = 1 ,18718.2 ,247,247.2,242
XS GIS Cut Line= 3
     2299202.175      397370.598     2299590.853      397219.276
     2299727.801       397240.85
#Sta/Elev= 30
       0     630    87.4  625.85    99.3  624.67   111.2  622.37   119.2  619.96
   131.1  615.36     151   605.5   158.9  600.26   166.8  593.88   170.8  591.99
   174.8  591.53   186.7  592.87   202.6  593.56   222.4   592.6   242.3  593.31
   262.2  591.94     294  592.33   305.9  590.47   313.8  591.05  316.54  592.46
  321.04595.9115   325.7  598.68  333.21600.0391   349.6  601.45   369.4  601.69
   401.2  604.46  435.23616.8881   452.8  623.23   492.4  638.82   555.7     660
#Mann= 6 ,-1 , 0
       0     .12       0     294    .045       0  316.54     .06       0
  321.04     .12       0  333.21    .016       0  435.23     .12       0
Bank Sta=294,316.54
XS Rating Curve= 0 ,0
Exp/Cntr=0.3,0.1

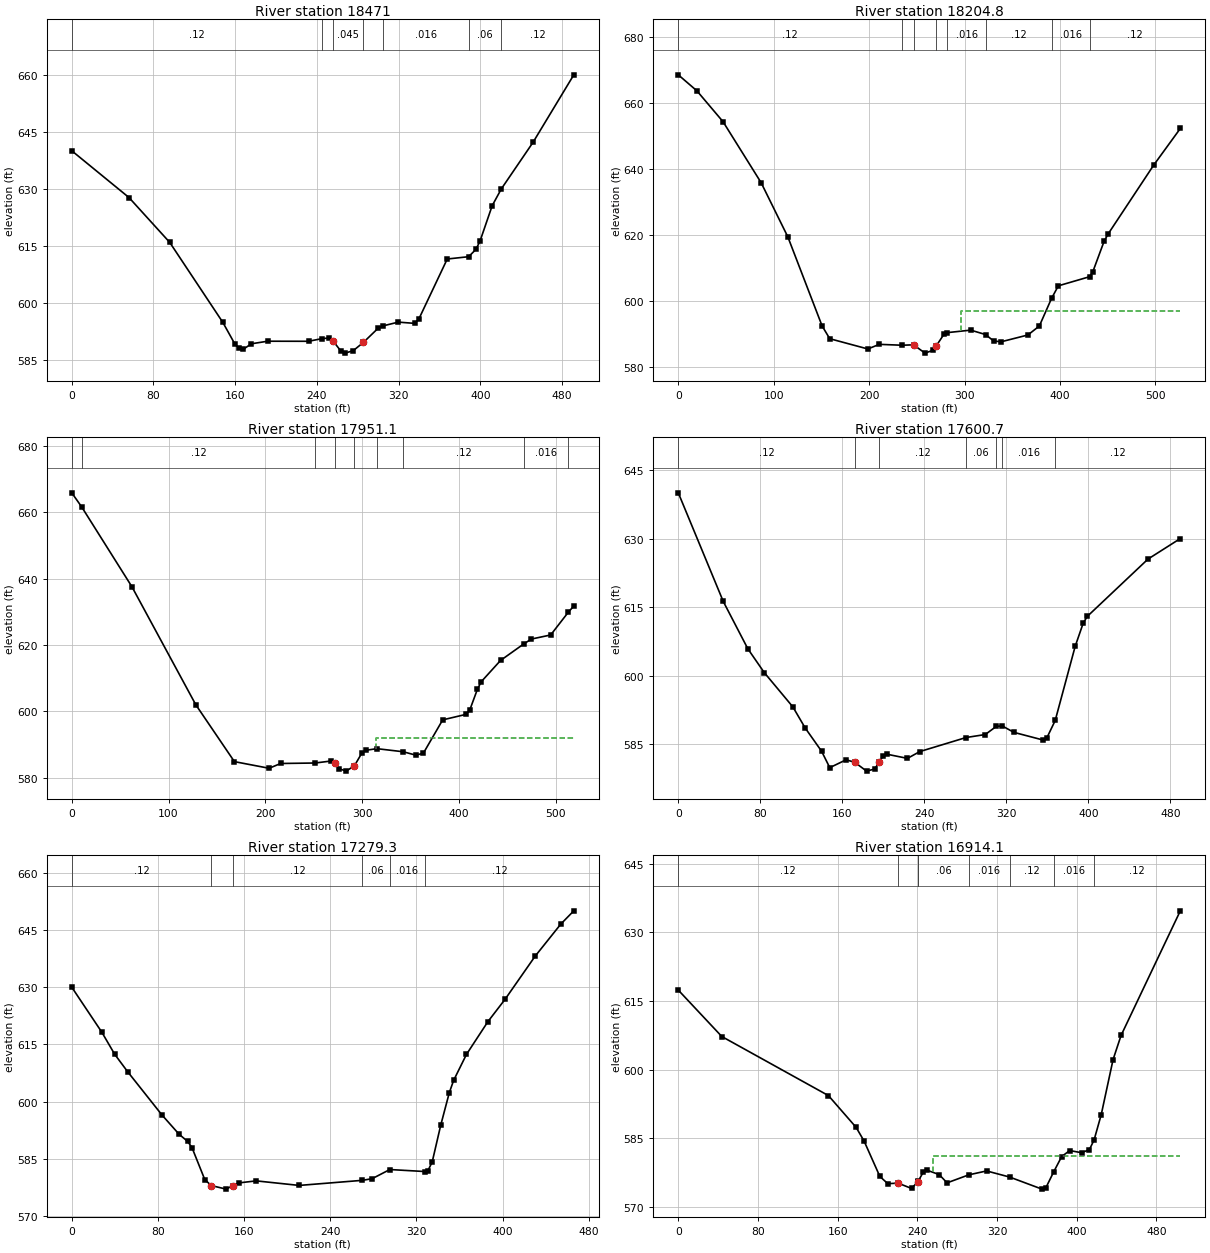
Type RM Length L Ch R = 1 ,18471   ,265.4,266.2,266.6
XS GIS Cut Line= 2
     2299307.605      397581.046     2299757.519      397383.132
#Sta/Elev= 30
       0     640      56  627.68    95.9  615.86   147.9  594.78   159.8  589.02
   163.8     588   167.8  587.67   175.8  589.14   191.8  589.82   231.8   589.8
  244.73590.4865   251.8  590.67   255.8  589.89   263.7  587.14   267.7  586.68
   275.7  587.36   285.5   589.5   299.7  593.18  304.91593.8729   319.7  594.85
   335.7  594.52   339.7  595.62   367.6  611.48   388.5612.0875   395.6  613.99
   399.6  616.13   411.6  625.53  420.52629.9474   451.6  642.23   491.5  660.01
#Mann= 7 ,-1 , 0
       0     .12       0  244.73     .06       0   255.8    .045       0
   285.5     .06       0  304.91    .016       0   388.5     .06       0
  420.52     .12       0
Bank Sta=255.8,285.5
XS Rating Curve= 0 ,0
Exp/Cntr=0.3,0.1

Type RM Length L Ch R = 1 ,18204.8 ,252.6,253.7,254.8
XS GIS Cut Line= 3
     2299414.277      397831.075     2299442.503      397804.232
     2299892.837      397618.829
#Sta/Elev= 30
       0  668.57    19.5  663.72    46.9  654.36    86.8  635.88   114.8  619.45
   150.7  592.45   158.7  588.59   198.6  585.48   210.6  586.88  234.55586.6105
   246.5  586.74   258.5  584.22   266.5  585.05   270.5   586.5   278.5  590.01
  282.06 590.439   306.4  591.19  321.97589.8494   330.4   587.9   338.3  587.66
   366.3  589.72   378.3  592.44  391.09600.8052   398.2  604.62  431.15607.3998
   434.2  608.78   446.1  618.08   450.1  620.22     498  641.16     526  652.31
#Mann= 8 ,-1 , 0
       0     .12       0  234.55     .06       0   246.5    .045       0
   270.5     .06       0  282.06    .016       0  321.97     .12       0
  391.09    .016       0  431.15     .12       0
#XS Ineff= 2 , 0
                          296.53          597.09
Permanent Ineff=
       F       F
Bank Sta=246.5,270.5
XS Rating Curve= 0 ,0
Exp/Cntr=0.3,0.1

Type RM Length L Ch R = 1 ,17951.1 ,319.4,350.4,347.7
XS GIS Cut Line= 3
     2299459.656       397983.12     2299584.506      398012.284
     2299952.074       397879.83
#Sta/Elev= 30
       0  665.86   10.23661.6219    62.2  637.56   128.2  602.03   168.1   584.9
     204   582.9   215.9  584.34  251.59584.4863   267.8  585.08   272.2  584.44
   275.7  582.83   283.7  582.04   292.2  583.68   299.6  587.36   303.6   588.3
  315.32588.8058  342.57587.8745   355.5  586.86   363.4  587.43   383.4  597.48
   407.3  599.12   411.3  600.39   419.2  606.64   423.2  608.96   443.2  615.38
  467.34620.3834   475.1  621.82     495  623.05  513.36629.9526   518.9  631.77
#Mann= 9 ,-1 , 0
       0    .016       0   10.23     .12       0  251.59     .06       0
   272.2    .045       0   292.2     .12       0  315.32    .016       0
  342.57     .12       0  467.34    .016       0  513.36     .12       0
#XS Ineff= 2 , 0
                          314.25          592.12
Permanent Ineff=
       F       F
Bank Sta=272.2,292.2
XS Rating Curve= 0 ,0
Exp/Cntr=0.3,0.1

Type RM Length L Ch R = 1 ,17600.7 ,331.7,321.3,308.2
XS GIS Cut Line= 3
     2299520.395      398232.817     2299890.607      398150.044
     2299997.093      398179.559
#Sta/Elev= 30
       0     640    43.9  616.21    67.9  605.84    83.9  600.64   111.8  593.13
   123.8  588.52   139.8  583.43   147.8  579.83   163.7  581.55   172.1  581.02
   183.7  579.07   191.7  579.54   195.7  580.97   199.7  582.31   203.6  582.77
   223.6  581.86   235.6  583.35   280.8586.4297   299.5  587.08  310.27588.8685
  316.04588.9662   327.4  587.56   355.4  585.91   359.4  586.26  367.74 590.155
   387.2  606.37   395.1   611.5   399.1  612.96   458.3   625.5   489.8  629.99
#Mann= 7 ,-1 , 0
       0     .12       0   172.1    .045       0   195.7     .12       0
   280.8     .06       0  310.27     .12       0  316.04    .016       0
  367.74     .12       0
Bank Sta=172.1,195.7
XS Rating Curve= 0 ,0
Exp/Cntr=0.3,0.1

Type RM Length L Ch R = 1 ,17279.3 ,367.8,365.2,360.3
XS GIS Cut Line= 2
     2299742.448      398542.203     2300108.114      398253.096
#Sta/Elev= 30
       0     630    27.9  618.22    39.8  612.46    51.8   607.9    83.7  596.56
    99.6  591.51   107.6  589.61   111.6  588.02   123.5  579.63   129.5  578.06
   143.4  577.12   149.5  578.03   155.4  578.76   171.3  579.28   211.2  578.09
  269.71  579.42   278.9  579.85  295.36582.2512  328.09581.7247   330.7  581.94
   334.7  584.23   342.6  593.84   350.6  602.39   354.6  605.59   366.5  612.39
   386.5  621.01   402.4  626.84   430.3  638.12   454.2  646.55   466.2     650
#Mann= 6 ,-1 , 0
       0     .12       0   129.5    .045       0   149.5     .12       0
  269.71     .06       0  295.36    .016       0  328.09     .12       0
Bank Sta=129.5,149.5
XS Rating Curve= 0 ,0
Exp/Cntr=0.3,0.1

Type RM Length L Ch R = 1 ,16914.1 ,95.1,94.6,94.6
XS GIS Cut Line= 2
     2299990.311      398800.402     2300332.114      398429.856
#Sta/Elev= 30
       0  617.39    43.7  607.26   150.8  594.36   178.6  587.42   186.6  584.43
   202.4  576.72   210.4  575.14   220.7  575.26   234.2   574.1   240.7   575.6
  240.96575.7189   246.1  577.69   250.1  578.06     262  577.12   269.9  575.32
  291.73  577.07   309.6  577.92  332.82 576.578   365.2  573.95   369.2  574.29
  376.86577.6794     385  581.06     393  582.37   404.9   581.9   412.8  582.57
  417.56584.7097   424.7  590.22   436.6  602.24   444.6  607.49   504.1  634.69
#Mann= 8 ,-1 , 0
       0     .12       0   220.7    .045       0   240.7     .12       0
  240.96     .06       0  291.73    .016       0  332.82     .12       0
  376.86    .016       0  417.56     .12       0
#XS Ineff= 2 , 0
                          255.71          581.25
Permanent Ineff=
       F       F
Bank Sta=220.7,240.7
XS Rating Curve= 0 ,0
Exp/Cntr=0.3,0.1

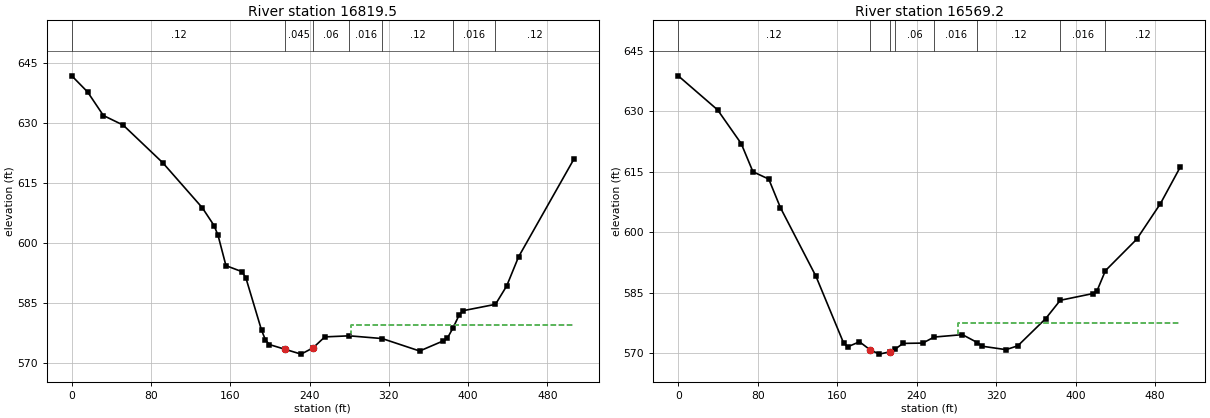
Type RM Length L Ch R = 1 ,16819.5 ,248.9,250.3,241.1
XS GIS Cut Line= 2
     2300067.134      398858.996     2300407.251      398483.358
#Sta/Elev= 30
       0  641.68      16  637.64    31.9  631.76    51.9  629.36    91.8  619.96
   131.7  608.71   143.6  604.25   147.6  601.82   155.6  594.23   171.6  592.74
   175.6  591.26   191.5  578.11   195.5  575.64   199.5   574.5   215.5   573.3
   231.4  572.11   243.4  573.66   255.4  576.42  280.15576.6843  313.23576.0028
   351.1  572.89   375.1  575.44   379.1  576.13   384.5 578.525     391  581.91
     395  582.97  427.61584.5596   438.9  589.14   450.9  596.42   506.7  620.84
#Mann= 7 ,-1 , 0
       0     .12       0   215.5    .045       0   243.4     .06       0
  280.15    .016       0  313.23     .12       0   384.5    .016       0
  427.61     .12       0
#XS Ineff= 2 , 0
                           281.9          579.49
Permanent Ineff=
       F       F
Bank Sta=215.5,243.4
XS Rating Curve= 0 ,0
Exp/Cntr=0.3,0.1

Type RM Length L Ch R = 1 ,16569.2 ,183.6,193.9,211.8
XS GIS Cut Line= 3
     2300188.228      398956.652     2300326.249      398896.756
     2300587.967      398657.173
#Sta/Elev= 30
       0  638.76    39.6  630.32    63.4  621.95    75.2  614.97    91.1  613.16
   102.9  606.04   138.6  589.05   166.4  572.53   170.4  571.55   182.4  572.81
     193  570.84   202.3  569.75     213  570.32  218.54571.0199   226.2  572.41
   246.1  572.49  257.55573.9844     286  574.58  300.93572.6295   305.9  571.71
   329.9  570.86   341.8  571.82   369.7  578.53  384.49583.1003   417.6  584.78
   421.6  585.52  429.93590.4505   461.4  598.24   485.3  607.07   505.3  616.16
#Mann= 8 ,-1 , 0
       0     .12       0     193    .045       0     213     .12       0
  218.54     .06       0  257.55    .016       0  300.93     .12       0
  384.49    .016       0  429.93     .12       0
#XS Ineff= 2 , 0
                          281.13          577.55
Permanent Ineff=
       F       F
Bank Sta=193,213
XS Rating Curve= 0 ,0
Exp/Cntr=0.3,0.1