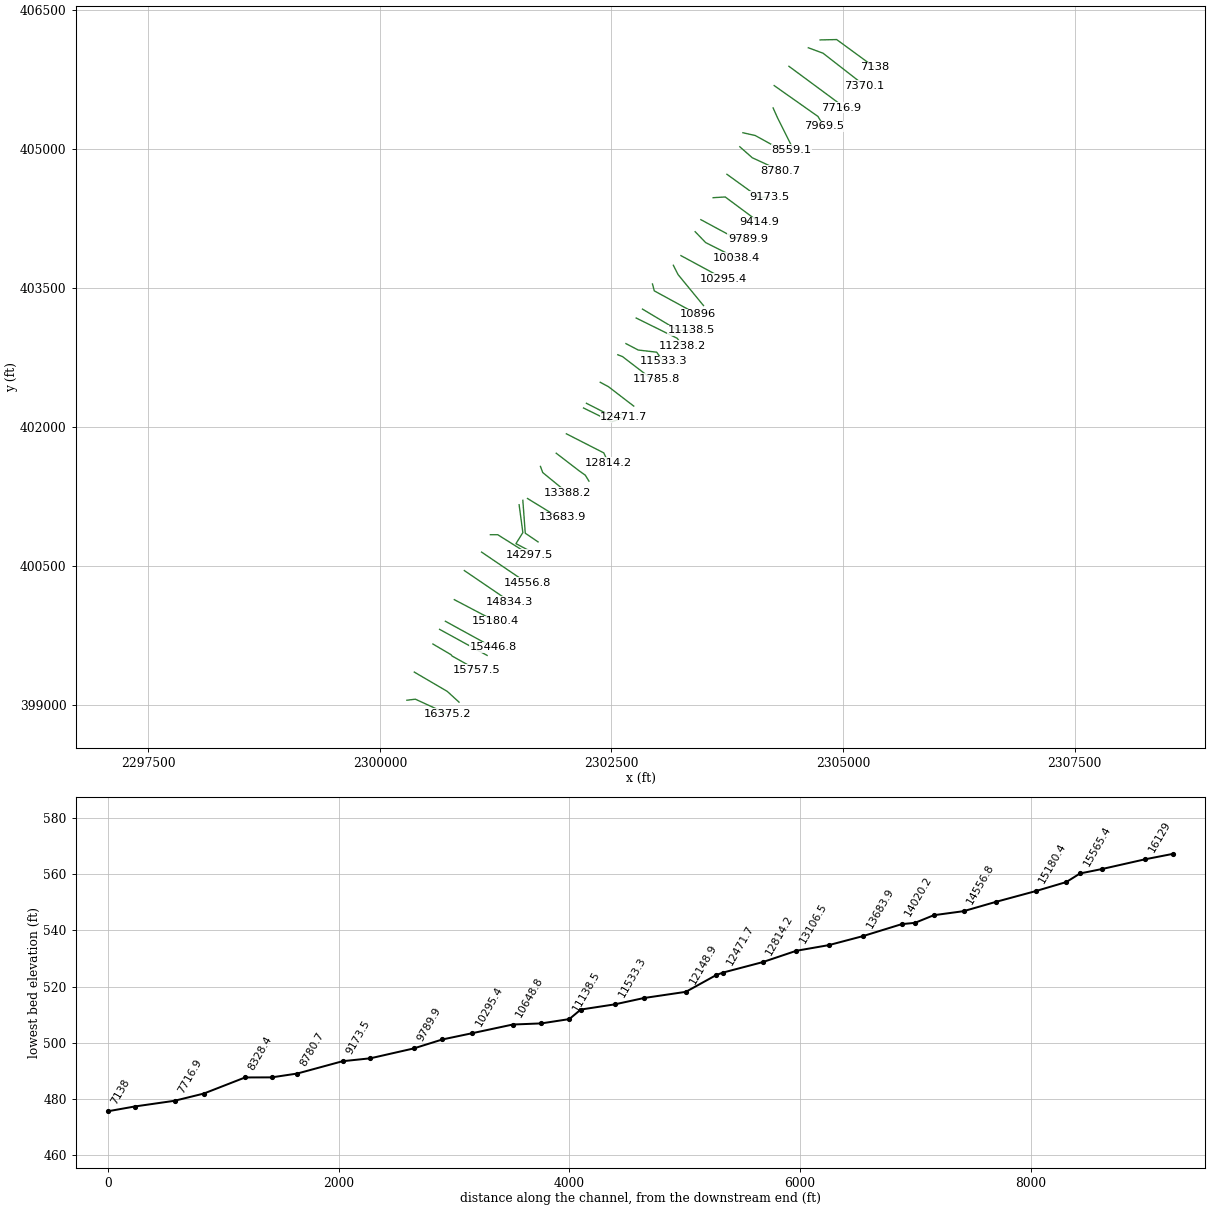
HEC-RAS study LONGHOLLOW.prj: LONGHOLLOW

--- LONGHOLLOW.g01 (geometry) --- (continued)

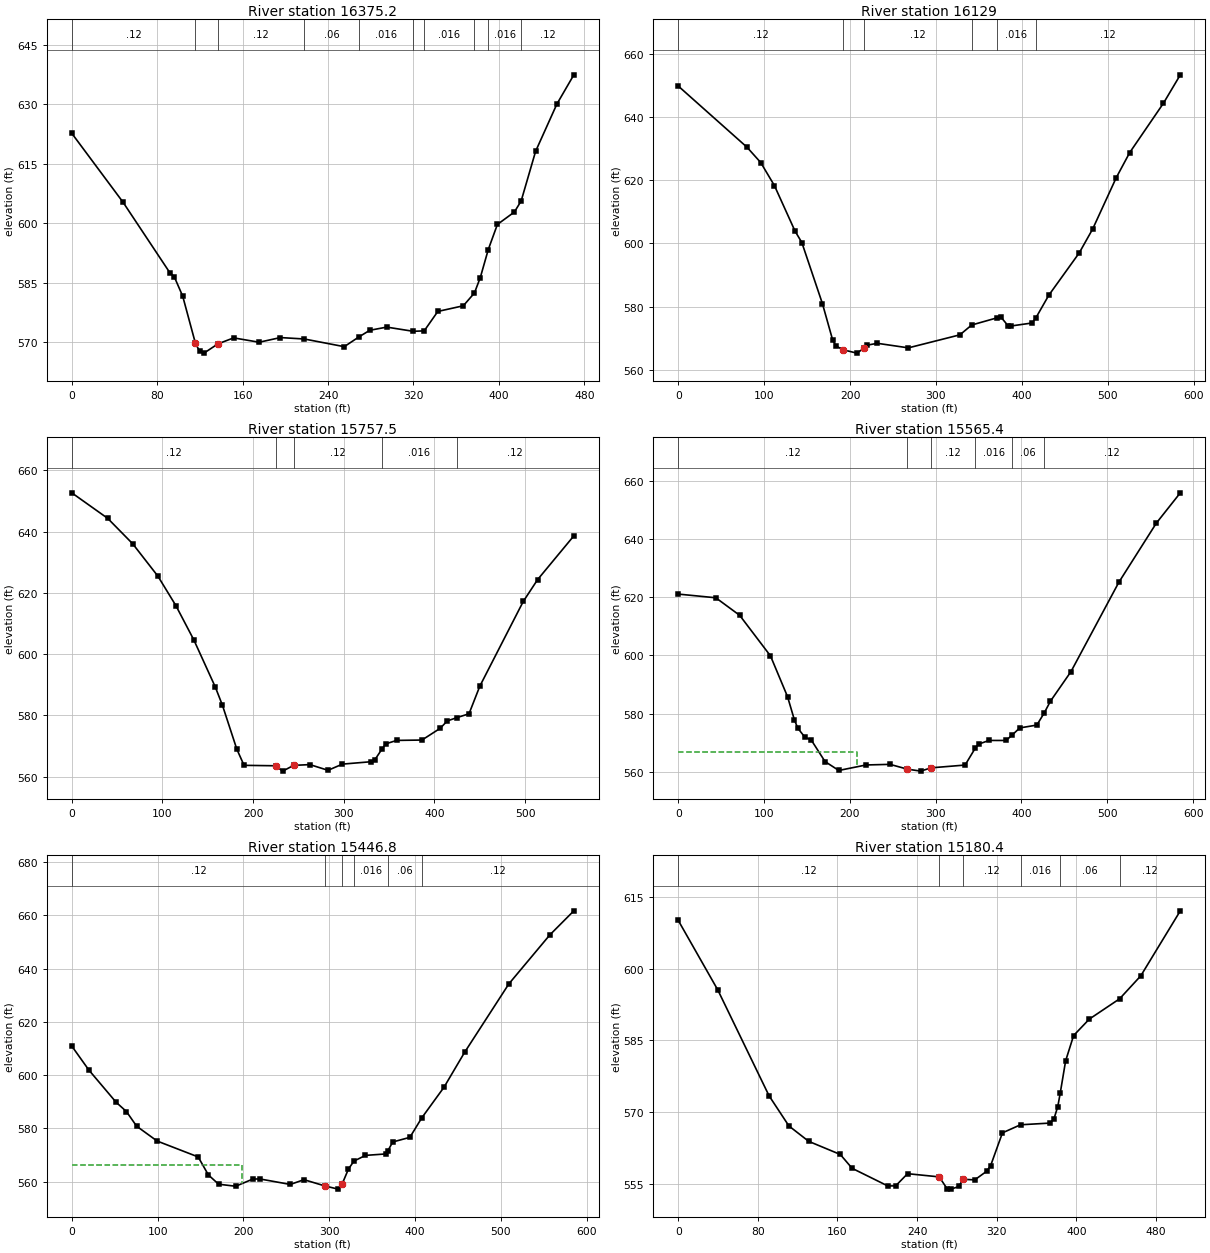
Type RM Length L Ch R = 1 ,16375.2 ,248.4,246.2,243.6
XS GIS Cut Line= 3
     2300292.394      399050.402     2300383.649      399061.405
     2300727.399      398903.419
#Sta/Elev= 30
       0  622.71      48  605.31    91.9  587.48    95.9  586.53   103.9  581.57
   115.8  569.67   119.8  567.66   123.8  567.19   136.9  569.53   151.6  571.04
   175.5  569.94   195.4  571.12  217.77570.7604   255.2  568.82  268.99571.2994
   279.1  572.96     295  573.76  319.83572.6987  330.07572.8164   342.8  577.72
   366.7  579.15   377.1582.3846   382.6  586.28  390.06 593.351   398.6  599.69
   414.5  602.83  420.86605.6238   434.4  618.17   454.3  630.09   470.2  637.48
#Mann= 10 ,-1 , 0
       0     .12       0   115.8    .045       0   136.9     .12       0
  217.77     .06       0  268.99    .016       0  319.83     .12       0
  330.07    .016       0   377.1     .12       0  390.06    .016       0
  420.86     .12       0
Bank Sta=115.8,136.9
XS Rating Curve= 0 ,0
Exp/Cntr=0.3,0.1

Type RM Length L Ch R = 1 ,16129   ,372.7,371.5,367.2
XS GIS Cut Line= 3
     2300371.822      399353.788     2300727.382      399145.987
     2300854.894      399029.569
#Sta/Elev= 30
       0  649.91      80  630.52      96  625.66     112  618.33   135.9  603.95
   143.9  600.28   167.9  580.88   179.9  569.25   183.9  567.44   191.9  566.29
   207.9  565.22     216  566.69   219.9  567.75   231.9  568.33   267.9  566.89
   327.9  571.02  341.63574.1357  371.45576.4371   375.8   576.6   383.8  573.96
   387.8  573.84   411.8  574.77  415.96576.2139   431.4  583.58   466.8  596.99
   482.5  604.59   509.9  620.84   525.6  628.81   564.9  644.47   584.5  653.46
#Mann= 6 ,-1 , 0
       0     .12       0   191.9    .045       0     216     .12       0
  341.63     .06       0  371.45    .016       0  415.96     .12       0
Bank Sta=191.9,216
XS Rating Curve= 0 ,0
Exp/Cntr=0.3,0.1

Type RM Length L Ch R = 1 ,15757.5 ,187.9,192.1,195.7
XS GIS Cut Line= 4
      2300573.21      399656.348     2300767.676      399542.061
     2300781.544       399526.14     2301049.556        399376.4
#Sta/Elev= 30
       0  652.66    39.6  644.33    67.3  635.98      95  625.44   114.8  615.84
   134.6  604.64   158.3  589.24   166.2  583.25     182  568.96     190  563.67
   224.7  563.53   232.6  561.78   244.7  563.66   262.6  563.91   282.6  562.05
   298.5  564.07   330.4  564.86   334.4  565.56   342.3 569.067   346.4   570.7
   358.3  571.81   386.2  571.93   406.2  575.74   414.1  578.17   424.5 579.226
   438.1  580.51     450  589.52   497.9  617.18   513.8  624.35   553.7  638.61
#Mann= 5 ,-1 , 0
       0     .12       0   224.7    .045       0   244.7     .12       0
   342.3    .016       0   424.5     .12       0
Bank Sta=224.7,244.7
XS Rating Curve= 0 ,0
Exp/Cntr=0.3,0.1

Type RM Length L Ch R = 1 ,15565.4 ,118.3,118.6,117.5
XS GIS Cut Line= 2
     2300645.259      399814.725      2301158.28      399533.475
#Sta/Elev= 30
       0  621.12    43.8  619.85    71.6  613.81   107.5  599.85   127.4   585.8
   135.3  577.89   139.3  574.99   147.3  571.97   155.2  570.81   171.1  563.48
   187.1  560.42   218.9  562.31   246.8  562.52     267  560.87   282.6  560.19
   294.5  561.32   334.3  562.28   346.1 568.075   350.2   569.5   362.2  570.75
   382.1  570.74  389.35 572.675     398  575.06   417.9  576.04  426.27580.0919
   433.8  584.28   457.7  594.45   513.4  625.15   557.2  645.56   585.1  655.97
#Mann= 6 ,-1 , 0
       0     .12       0     267    .045       0   294.5     .12       0
   346.1    .016       0  389.35     .06       0  426.27     .12       0
#XS Ineff= 2 , 0
          207.96  566.89
Permanent Ineff=
       F       F
Bank Sta=267,294.5
XS Rating Curve= 0 ,0
Exp/Cntr=0.3,0.1

Type RM Length L Ch R = 1 ,15446.8 ,265.5,266.4,266.6
XS GIS Cut Line= 2
     2300707.759      399901.965      2301220.78      399620.715
#Sta/Elev= 30
       0  610.91    19.9   601.9    51.7  589.78    63.7   586.3    75.6  580.79
    99.5  575.21   147.3  569.24   159.2  562.48   171.1  558.99     191  558.22
   210.9  560.91   218.9  560.98   254.7   558.9   270.6  560.69   295.1  558.33
   310.4  557.14   315.1  559.07   322.4  564.67  328.84567.6797   342.3  569.82
   366.2  570.37  368.41571.6053   374.1  574.86     394   576.6  407.94583.9513
   433.8  595.44   457.7   608.5   509.4  634.29   557.2  652.71   585.1  661.73
#Mann= 6 ,-1 , 0
       0     .12       0   295.1    .045       0   315.1     .12       0
  328.84    .016       0  368.41     .06       0  407.94     .12       0
#XS Ineff= 2 , 0
          197.95  566.07
Permanent Ineff=
       F       F
Bank Sta=295.1,315.1
XS Rating Curve= 0 ,0
Exp/Cntr=0.3,0.1

Type RM Length L Ch R = 1 ,15180.4 ,344.4,346.1,342.7
XS GIS Cut Line= 2
     2300804.113      400135.038     2301250.728      399900.663
#Sta/Elev= 30
       0  610.11    39.7  595.58    91.3  573.41   111.2  567.12   131.1   563.9
   162.8  561.16   174.7  558.26   210.5  554.58   218.4  554.59   230.4  557.14
   262.2  556.47   270.1     554     274  553.91     282  554.46     286  555.96
   297.9  555.85   309.8  557.64   313.8   558.8   325.7  565.68  343.87567.3667
   373.3  567.72   377.3   568.5   381.3  571.17  383.76573.9896   389.2  580.75
   397.2  586.03     413  589.47   443.4593.7105   464.7  598.52   504.4  612.11
#Mann= 6 ,-1 , 0
       0     .12       0   262.2    .045       0     286     .12       0
  343.87    .016       0  383.76     .06       0   443.4     .12       0
Bank Sta=262.2,286
XS Rating Curve= 0 ,0
Exp/Cntr=0.3,0.1

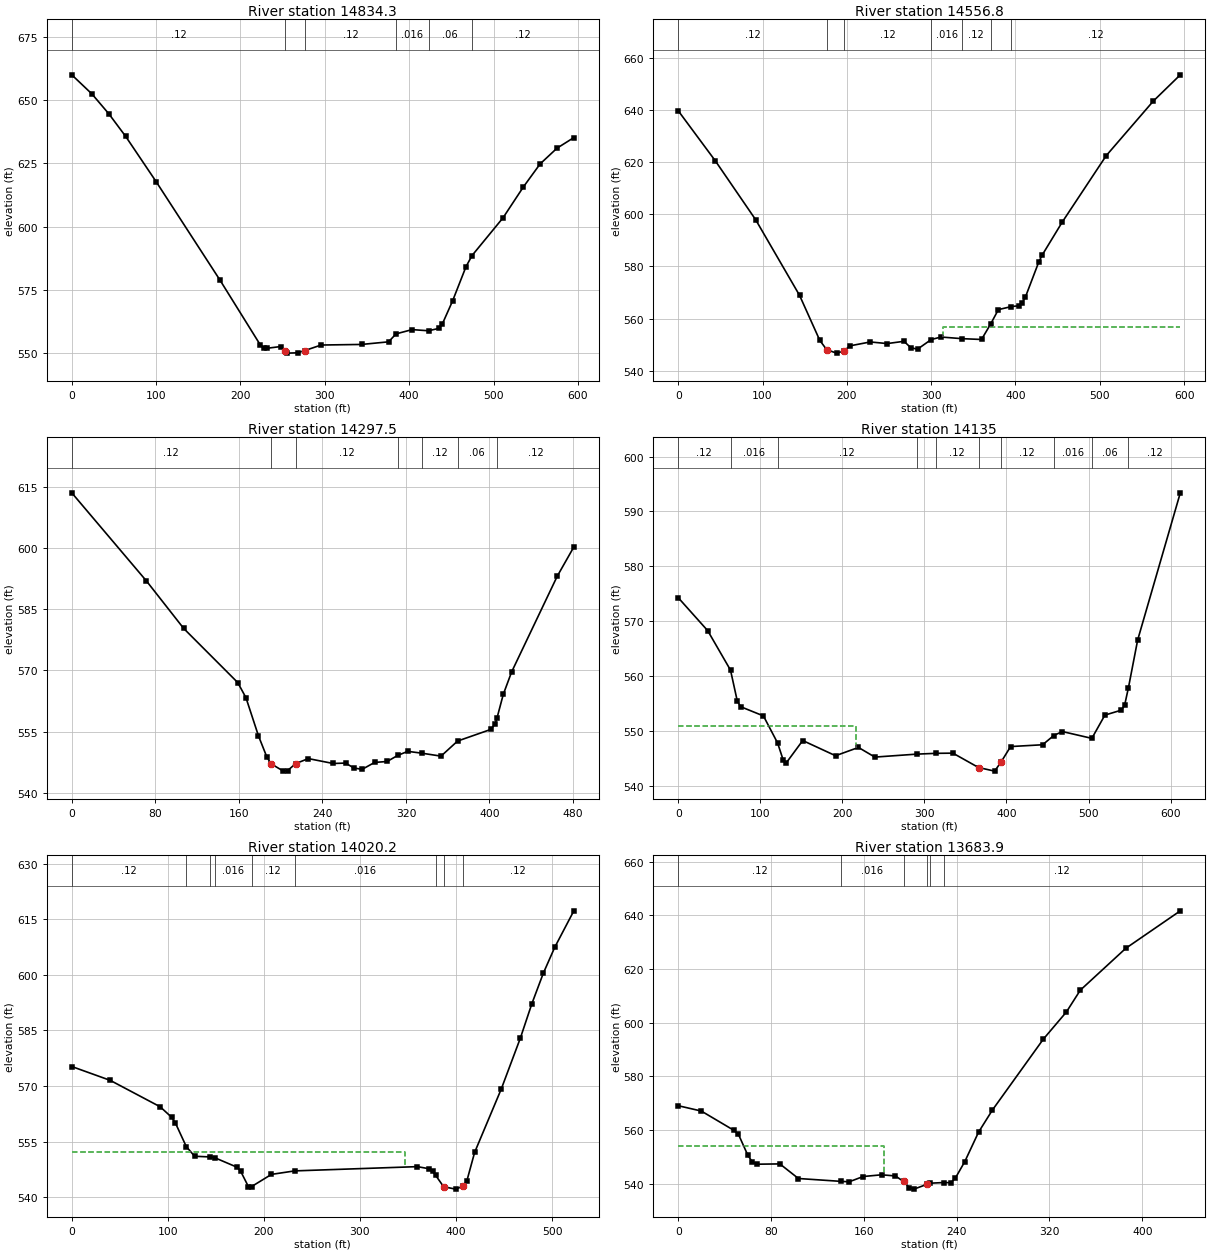
Type RM Length L Ch R = 1 ,14834.3 ,276.8,277.6,276.9
XS GIS Cut Line= 2
     2300912.186       400448.84     2301404.374      400114.204
#Sta/Elev= 30
       0  660.03      24  652.44    43.9  644.64    63.9   635.7    99.9  617.88
   175.8  578.87   223.7  553.21   227.7  552.17   231.7     552   247.7  552.67
  253.03  550.94   255.6  550.07   267.6  550.19   276.2  551.08   295.6  553.27
   343.5   553.5   375.5  554.53  384.48557.6807   403.4  559.36  422.91558.9065
   435.4  559.87   439.4  561.67   451.4  570.66   467.4  584.26  474.53588.6384
   511.3  603.56   535.3   615.7   555.2  624.82   575.2  631.04   595.2  635.23
#Mann= 6 ,-1 , 0
       0     .12       0  253.03    .045       0   276.2     .12       0
  384.48    .016       0  422.91     .06       0  474.53     .12       0
Bank Sta=253.03,276.2
XS Rating Curve= 0 ,0
Exp/Cntr=0.3,0.1

Type RM Length L Ch R = 1 ,14556.8 ,258.4,259.3,260.1
XS GIS Cut Line= 2
     2301098.384      400648.058     2301591.407       400314.07
#Sta/Elev= 30
       0  639.63      44  620.45    91.9  597.86   143.9  568.92   167.9  551.67
   176.1   548.1   187.8  546.79   196.1  547.54   203.8  549.59   227.8  551.07
   247.8  550.45   267.8  551.32   275.8  548.87   283.8   548.3  300.07551.9998
   311.7  552.96  336.34 552.336   359.7  552.02  370.43557.8768   379.7  563.46
  395.25564.6266   403.7  564.93   407.7  565.99   411.6  568.12   427.6  581.69
   431.6  584.32   455.6  597.06   507.6  622.43   563.5  643.35   595.5   653.4
#Mann= 7 ,-1 , 0
       0     .12       0   176.1    .045       0   196.1     .12       0
  300.07    .016       0  336.34     .12       0  370.43     .06       0
  395.25     .12       0
#XS Ineff= 2 , 0
                          314.25          556.84
Permanent Ineff=
       F       F
Bank Sta=176.1,196.1
XS Rating Curve= 0 ,0
Exp/Cntr=0.3,0.1

Type RM Length L Ch R = 1 ,14297.5 ,205.4,162.5,119.5
XS GIS Cut Line= 3
     2301193.436      400835.558     2301272.863      400835.558
     2301612.707      400622.017
#Sta/Elev= 30
       0  613.47    71.5   591.9   107.2  580.27   158.9  567.04   166.8  563.33
   178.8  553.97   186.7  548.88   190.7  547.17   202.6  545.35   206.6  545.47
   214.5   547.2   226.5  548.42   250.3  547.22   262.2  547.32   270.2  546.11
   278.1  545.79     290  547.48     302  547.71  312.33549.2256   321.8  550.19
  334.95549.7505   353.6  549.02  369.45552.7094   401.3  555.56   405.3  556.87
  407.18558.3129   413.2  564.12   421.2  569.62   464.9  593.06   480.8  600.22
#Mann= 7 ,-1 , 0
       0     .12       0   190.7    .045       0   214.5     .12       0
  312.33    .016       0  334.95     .12       0  369.45     .06       0
  407.18     .12       0
Bank Sta=190.7,214.5
XS Rating Curve= 0 ,0
Exp/Cntr=0.3,0.1

Type RM Length L Ch R = 1 ,14135   ,72.5,114.8,154
XS GIS Cut Line= 4
     2301503.668      401159.116     2301544.032      400858.335
     2301469.478      400739.204     2301617.915      400661.079
#Sta/Elev= 30
       0  574.27    35.9  568.26    63.7561.0615    71.9  555.46    75.9   554.4
   103.8  552.71  121.07547.7781   127.8  544.71   131.8  544.18   151.7  548.22
   191.7  545.45   219.6  546.96   239.6   545.2  290.51545.7397   314.1545.8854
   334.7  545.92   365.9   543.3   385.5  542.64   393.3  544.28     405  547.12
     444  547.45  457.57549.1306     468  549.86  503.99 548.616   519.9  552.86
   539.9  553.76   543.9  554.64  548.64557.8903   559.8  566.54   611.8   593.4
#Mann= 10 ,-1 , 0
       0     .12       0    63.7    .016       0  121.07     .12       0
  290.51    .016       0   314.1     .12       0   365.9    .045       0
   393.3     .12       0  457.57    .016       0  503.99     .06       0
  548.64     .12       0
#XS Ineff= 2 , 0
          216.56  550.87
Permanent Ineff=
       F       F
Bank Sta=365.9,393.3
XS Rating Curve= 0 ,0
Exp/Cntr=0.3,0.1

Type RM Length L Ch R = 1 ,14020.2 ,334.7,336.3,337.2
XS GIS Cut Line= 3
     2301543.697      401206.652     2301570.074      400851.824
     2301708.095      400758.074
#Sta/Elev= 30
       0  575.27      40  571.54      92  564.41   103.9  561.59   107.9  560.02
  119.23553.6564   127.9  551.05  143.54550.8772  149.29550.6088   171.9  548.11
   175.9  546.97   183.9  542.85  187.17542.8663   207.9  546.16  232.15547.1019
   359.8  548.25   371.7  547.69   375.7  547.09  378.76545.9209   387.1  542.84
   399.5  542.18   407.1  542.92   411.4  544.49   419.4  552.09   447.2  569.24
     467  582.93     479  592.23   490.9  600.44   502.8  607.44   522.7  617.29
#Mann= 9 ,-1 , 0
       0     .12       0  119.23    .016       0  143.54     .08       0
  149.29    .016       0  187.17     .12       0  232.15    .016       0
  378.76     .12       0   387.1    .045       0   407.1     .12       0
#XS Ineff= 2 , 0
           346.6  552.24
Permanent Ineff=
       F       F
Bank Sta=387.1,407.1
XS Rating Curve= 0 ,0
Exp/Cntr=0.3,0.1

Type RM Length L Ch R = 1 ,13683.9 ,298.8,295.7,291.9
XS GIS Cut Line= 3
     2301594.478      401226.183     2301890.051      401045.194
     2301973.384      401023.058
#Sta/Elev= 30
       0  569.01    19.9  567.02    47.8  559.88    51.8  558.44    59.8  550.73
    63.7  548.12    67.7  547.21    87.6  547.32   103.6  541.88  140.32540.8102
   147.4  540.66   159.4  542.62   175.3  543.26   187.2  542.83   194.2  540.78
   199.2  538.51   203.2  537.92   214.2  539.68   216.6  540.12  228.85540.3713
     235   540.3     239  542.11     247  548.17   258.9  559.17   270.9  567.45
   314.7  593.81   334.6  603.95   346.6  612.08   385.8  627.68   432.8  641.65
#Mann= 6 ,-1 , 0
       0     .12       0  140.32    .016       0   194.2    .045       0
   214.2     .12       0   216.6     .06       0  228.85     .12       0
#XS Ineff= 2 , 0
          177.79  554.11
Permanent Ineff=
       F       F
Bank Sta=194.2,214.2
XS Rating Curve= 0 ,0
Exp/Cntr=0.3,0.1

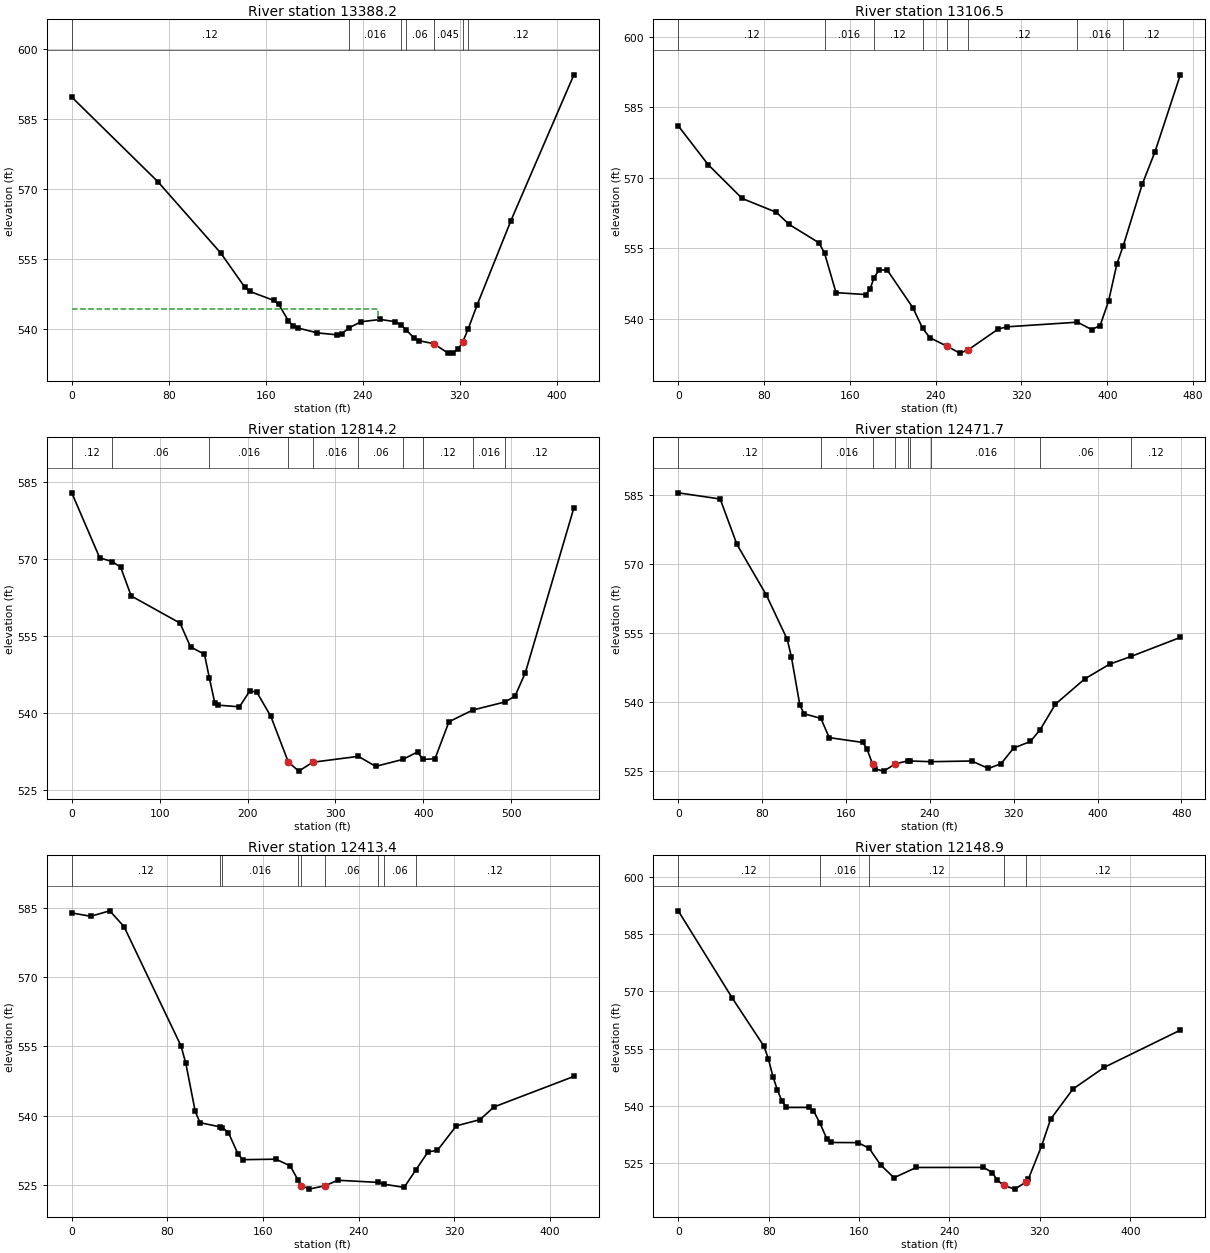
Type RM Length L Ch R = 1 ,13388.2 ,276.9,281.7,282.9
XS GIS Cut Line= 3
     2301733.801      401572.538      2301758.54      401506.131
     2302024.165      401288.683
#Sta/Elev= 30
       0  589.63    70.9  571.52   122.8  556.21   142.7  548.86   146.7  547.97
   166.7  546.01   170.7  545.17   178.6  541.68   182.6  540.54   186.6   540.1
   202.6  539.06   218.6  538.65   222.6  538.85  228.48540.1056   238.5  541.45
   254.5  541.94   266.4  541.48  271.61540.7778  275.55539.7705   282.4  537.94
   286.4  537.39   298.4  536.75   310.4  534.72   314.4  534.83   318.3   535.5
   322.3  537.03  326.79539.8041   334.3  545.03   362.2  563.13   414.1  594.41
#Mann= 7 ,-1 , 0
       0     .12       0  228.48    .016       0  271.61     .12       0
  275.55     .06       0   298.4    .045       0   322.3     .06       0
  326.79     .12       0
#XS Ineff= 2 , 0
          252.89   544.2
Permanent Ineff=
       F       F
Bank Sta=298.4,322.3
XS Rating Curve= 0 ,0
Exp/Cntr=0.3,0.1

Type RM Length L Ch R = 1 ,13106.5 ,290.2,292.3,295.1
XS GIS Cut Line= 4
     2301904.374      401714.465     2302150.467      401525.663
     2302218.176      401477.485     2302257.238      401413.683
#Sta/Elev= 30
       0  581.04    27.8  572.81    59.6  565.59    91.5  562.65   103.4  560.07
   131.2  556.17  136.46553.9403   147.1  545.57     175  545.16     179  546.45
  182.37548.6103   186.9  550.35   194.8   550.4   218.7  542.38  227.87 537.988
   234.6  535.99   250.2  534.22   262.5  532.71   270.2  533.39   298.2  537.81
   306.2   538.3  372.22539.2888   385.4  537.72   393.3  538.56   401.2  543.76
     409  551.69  414.88555.5114   432.6  568.62   444.5  575.52   468.1  591.88
#Mann= 8 ,-1 , 0
       0     .12       0  136.46    .016       0  182.37     .12       0
  227.87     .06       0   250.2    .045       0   270.2     .12       0
  372.22    .016       0  414.88     .12       0
Bank Sta=250.2,270.2
XS Rating Curve= 0 ,0
Exp/Cntr=0.3,0.1

Type RM Length L Ch R = 1 ,12814.2 ,341.4,342.5,342.2
XS GIS Cut Line= 3
     2302013.749        401924.1     2302417.394      401718.371
     2302468.176        401611.6
#Sta/Elev= 30
       0  582.89    31.8  570.22   45.92569.4934    55.6  568.41    67.6   562.8
   123.2  557.51   135.1  552.88     151  551.43  156.63546.7526   162.9  541.85
   166.9  541.52   190.8   541.2   202.7  544.33   210.6  544.04   226.5  539.34
   246.4  530.44   258.3  528.67   274.2   530.4   326.1 531.549   345.8   529.6
  376.69530.9483   393.4   532.4  399.53530.9565   413.3  531.07   429.2  538.29
  456.33540.5731  492.98542.1508   504.3  543.27   516.1  547.84   571.3  579.93
#Mann= 10 ,-1 , 0
       0     .12       0   45.92     .06       0  156.63    .016       0
   246.4    .045       0   274.2    .016       0   326.1     .06       0
  376.69    .016       0  399.53     .12       0  456.33    .016       0
  492.98     .12       0
Bank Sta=246.4,274.2
XS Rating Curve= 0 ,0
Exp/Cntr=0.3,0.1

Type RM Length L Ch R = 1 ,12471.7 ,58.2,58.3,59.4
XS GIS Cut Line= 3
     2302199.197      402202.244     2302504.405      402052.649
     2302634.614       402101.26
#Sta/Elev= 30
       0  585.43      40  584.09      56  574.22      84  563.24     104  553.57
     108   549.7     116  539.31     120  537.44  136.06536.4227     144  532.25
     176   531.2     180   529.8  185.49  526.43   187.9  525.45   195.9  524.97
   207.1  526.54  218.95527.2066   221.4527.1713  241.04527.0186   279.9  527.17
   295.9  525.55   307.9  526.58   319.9  529.98   335.9  531.41  345.31534.0086
   359.8  539.52   387.6  544.98   411.4   548.2  432.18 549.908   478.9  554.02
#Mann= 9 ,-1 , 0
       0     .12       0  136.06    .016       0  185.49    .045       0
   207.1    .016       0  218.95     .12       0   221.4     .06       0
  241.04    .016       0  345.31     .06       0  432.18     .12       0
Bank Sta=185.49,207.1
XS Rating Curve= 0 ,0
Exp/Cntr=0.3,0.1

Type RM Length L Ch R = 1 ,12413.4 ,268.8,264.5,257.6
XS GIS Cut Line= 3
     2302230.447      402253.025     2302517.426      402107.336
     2302611.176       402136.85
#Sta/Elev= 30
       0  583.86    15.9  583.14    31.8  584.32    43.7  580.91    91.4  555.09
    95.4  551.35   103.3  540.93   107.3  538.49   123.8537.5895  125.99537.4417
   131.1  536.31   139.1  531.71     143  530.48   170.8  530.59   182.8  529.13
  189.47525.9985   192.2  524.87   198.7  524.11   212.2  524.87   222.5  526.03
  256.24 525.569  260.86525.1937   278.1  524.49  287.96528.2837     298  532.15
     306  532.52   321.8   537.8   341.5  539.14   353.3  541.89   420.1  548.49
#Mann= 9 ,-1 , 0
       0     .12       0   123.8     .08       0  125.99    .016       0
  189.47     .12       0   192.2    .045       0   212.2     .06       0
  256.24     .12       0  260.86     .06       0  287.96     .12       0
Bank Sta=192.2,212.2
XS Rating Curve= 0 ,0
Exp/Cntr=0.3,0.1

Type RM Length L Ch R = 1 ,12148.9 ,362.2,363.1,362.5
XS GIS Cut Line= 3
     2302379.405      402479.732     2302467.426      402432.713
     2302740.864      402223.077
#Sta/Elev= 30
       0  591.13    47.9  568.21    75.8  555.62    79.8  552.28    83.8  547.66
    87.8  544.06    91.8  541.24    95.8  539.54   115.6  539.55   119.6  538.74
  125.48535.3558   131.5  531.31   135.4  530.36   159.2  530.31  169.04528.8022
     179   524.5   190.9  521.11   210.7   523.8   270.1  523.82     278  522.47
     282  520.57     288  519.09   297.8  518.12     308  520.01   309.7  520.67
   321.6  529.49   329.5  536.46   349.3  544.38     377  550.07   444.3  559.83
#Mann= 5 ,-1 , 0
       0     .12       0  125.48    .016       0  169.04     .12       0
     288    .045       0     308     .12       0
Bank Sta=288,308
XS Rating Curve= 0 ,0
Exp/Cntr=0.3,0.1

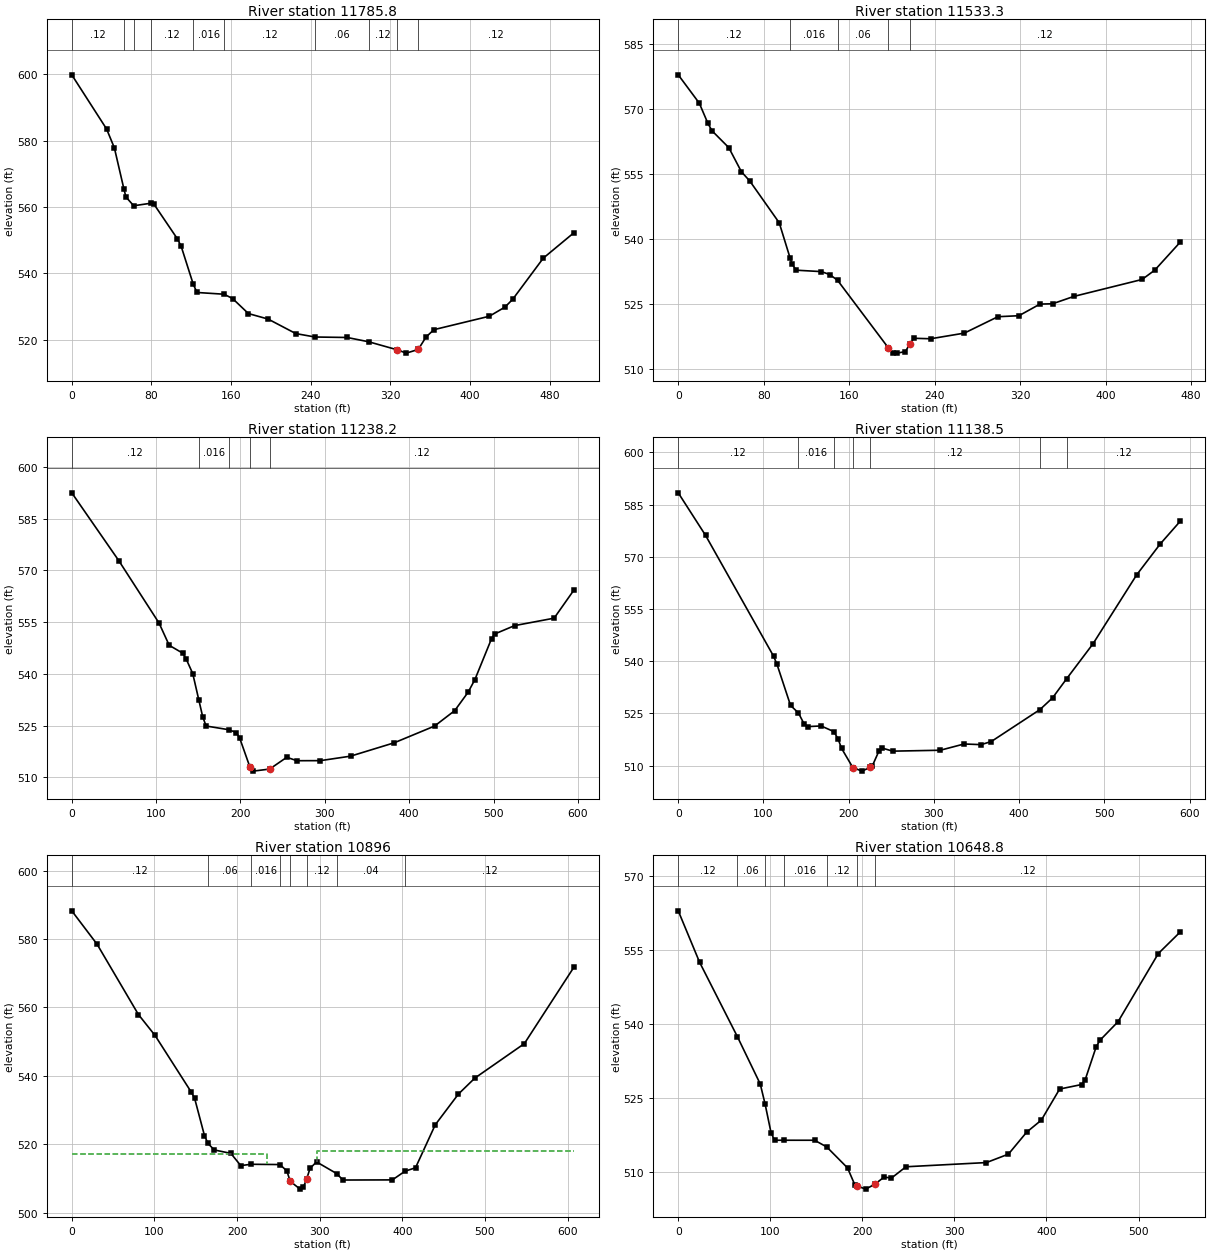
Type RM Length L Ch R = 1 ,11785.8 ,238.7,252.5,265.1
XS GIS Cut Line= 4
     2302568.989      402776.463      2302619.77      402756.931
     2302918.973      402527.823     2302990.864      402514.744
#Sta/Elev= 30
       0   599.9      35  583.54    42.8  577.85   52.48565.3096    54.4  563.04
   62.21560.3878   79.82561.1688    82.2  561.02     106  550.45   109.9  548.14
  122.06536.6697   125.8  534.22  152.91533.6983   161.5   532.4   177.4  527.86
   197.2   526.2     225  521.82  244.34520.7846   276.6  520.64  298.28519.3425
   326.8  516.93     336  515.92     348  517.03   355.9  520.81   363.8     523
   419.4  527.05   435.1  529.81   442.8  532.13   473.6  544.58   504.3  552.23
#Mann= 10 ,-1 , 0
       0     .12       0   52.48     .06       0   62.21     .08       0
   79.82     .12       0  122.06    .016       0  152.91     .12       0
  244.34     .06       0  298.28     .12       0   326.8    .045       0
     348     .12       0
Bank Sta=326.8,348
XS Rating Curve= 0 ,0
Exp/Cntr=0.3,0.1

Type RM Length L Ch R = 1 ,11533.3 ,302.4,295,286.3
XS GIS Cut Line= 4
     2302656.978      402896.756      2302789.79      402827.746
     2302989.009      402804.308     2303058.019      402706.652
#Sta/Elev= 30
       0  577.79    19.7  571.26    27.6   566.7    31.5  564.92    47.3  561.02
    59.1  555.46      67  553.31    94.5   543.7   104.7535.5563   106.4  534.26
   110.3  532.78   133.9  532.45   141.8  531.78  149.09530.4434   196.4  514.95
   200.8  513.76   204.7  513.67   212.6  514.02   216.4  515.68   220.5  517.09
   236.2  516.98   267.7  518.28   299.1  522.06   318.8  522.29   338.5  524.97
   350.3  525.04   370.2  526.74     434  530.64   445.9  532.79   469.8  539.26
#Mann= 5 ,-1 , 0
       0     .12       0   104.7    .016       0  149.09     .06       0
   196.4    .045       0   216.4     .12       0
Bank Sta=196.4,216.4
XS Rating Curve= 0 ,0
Exp/Cntr=0.3,0.1

Type RM Length L Ch R = 1 ,11238.2 ,101.7,99.8,97.8
XS GIS Cut Line= 3
     2302767.655      403172.798      2303210.43      402954.216
     2303271.561      402873.319
#Sta/Elev= 30
       0  592.52    55.8  572.83   103.5  554.74   115.5  548.31   131.4  546.04
   135.4  544.45   143.4  540.12   150.6532.4738   155.3  527.49   159.3   524.9
  186.32523.8236   195.1  522.99   199.1  521.38     211  513.13     215  511.82
   234.6  512.42   254.9  515.84   266.8  514.84   294.7  514.86   330.5  516.16
   382.3  520.04   430.1  524.89     454  529.37   469.9  534.72   477.9  538.37
   497.7  550.27   501.6  551.61     525  554.02   571.8  556.17   595.2   564.3
#Mann= 5 ,-1 , 0
       0     .12       0   150.6    .016       0  186.32     .12       0
     211    .045       0   234.6     .12       0
Bank Sta=211,234.6
XS Rating Curve= 0 ,0
Exp/Cntr=0.3,0.1

Type RM Length L Ch R = 1 ,11138.5 ,241.2,242.5,243.2
XS GIS Cut Line= 3
     2302835.363      403269.152     2303219.478      403039.985
     2303361.405      403041.288
#Sta/Elev= 30
       0  588.39      32  576.19   111.8  541.49   115.8  539.18   131.8  527.31
  141.07525.1422   147.8  521.94   151.8  521.22   167.7  521.41  182.69519.7766
   187.7   517.6   191.7  514.95   204.9  509.45   215.6  508.43   224.9  509.48
   227.6  509.84   235.6  514.24   239.6  515.04   251.6  514.17   307.5  514.43
   335.5  516.23   355.4  516.04   367.4  516.94  424.51526.1192   439.3  529.49
  455.73534.9557   486.7     545     538  564.83   565.6  573.69   589.2  580.26
#Mann= 7 ,-1 , 0
       0     .12       0  141.07    .016       0  182.69     .12       0
   204.9    .045       0   224.9     .12       0  424.51    .016       0
  455.73     .12       0
Bank Sta=204.9,224.9
XS Rating Curve= 0 ,0
Exp/Cntr=0.3,0.1

Type RM Length L Ch R = 1 ,10896   ,256.8,247.2,237.5
XS GIS Cut Line= 3
     2302943.436      403539.985     2302962.967      403465.767
     2303429.113       403211.86
#Sta/Elev= 30
       0  588.23    30.7  578.44    80.7  557.91   100.7  551.84   144.6  535.26
   148.6   533.5   160.6  522.54  164.84520.2462   172.5  518.35   192.5  517.35
   204.5  513.78  217.23514.1622  251.88514.0795   260.3  512.22   264.3   509.2
   276.3   506.9   280.3  507.46   284.3  509.88   288.3  512.96   296.2  514.86
  320.58511.4408   328.2  509.56     388   509.6  403.22512.1322     416  513.14
   439.9  525.71   467.9  534.68   487.8  539.35   547.7  549.42   607.6  571.73
#Mann= 8 ,-1 , 0
       0     .12       0  164.84     .06       0  217.23    .016       0
  251.88     .12       0   264.3    .045       0   284.3     .12       0
  320.58     .04       0  403.22     .12       0
#XS Ineff= 2 , 0
          236.33  517.22  296.53          518.11
Permanent Ineff=
       F       F
Bank Sta=264.3,284.3
XS Rating Curve= 0 ,0
Exp/Cntr=0.3,0.1

Type RM Length L Ch R = 1 ,10648.8 ,342.3,353.4,361.8
XS GIS Cut Line= 3
     2303168.697      403741.808     2303219.478      403641.548
     2303494.217      403306.913
#Sta/Elev= 30
       0  562.87    23.2  552.45   64.18537.4103    89.1  527.79   94.38523.7122
   100.8  517.94   104.6   516.4   114.9516.4025   148.1   516.4  161.31515.0458
   183.9   510.8   191.8  507.38   194.1  507.14   203.8   506.5   214.1  507.56
   223.6  508.94   231.6  508.74   247.4  511.03   334.8  511.88   358.7  513.59
   378.5  518.04   394.4  520.47   414.3  526.77   438.1  527.68   442.1  528.68
     454  535.32     458  536.63   477.8  540.42   521.5  554.22   545.4   558.6
#Mann= 7 ,-1 , 0
       0     .12       0   64.18     .06       0   94.38     .08       0
   114.9    .016       0  161.31     .12       0   194.1    .045       0
   214.1     .12       0
Bank Sta=194.1,214.1
XS Rating Curve= 0 ,0
Exp/Cntr=0.3,0.1

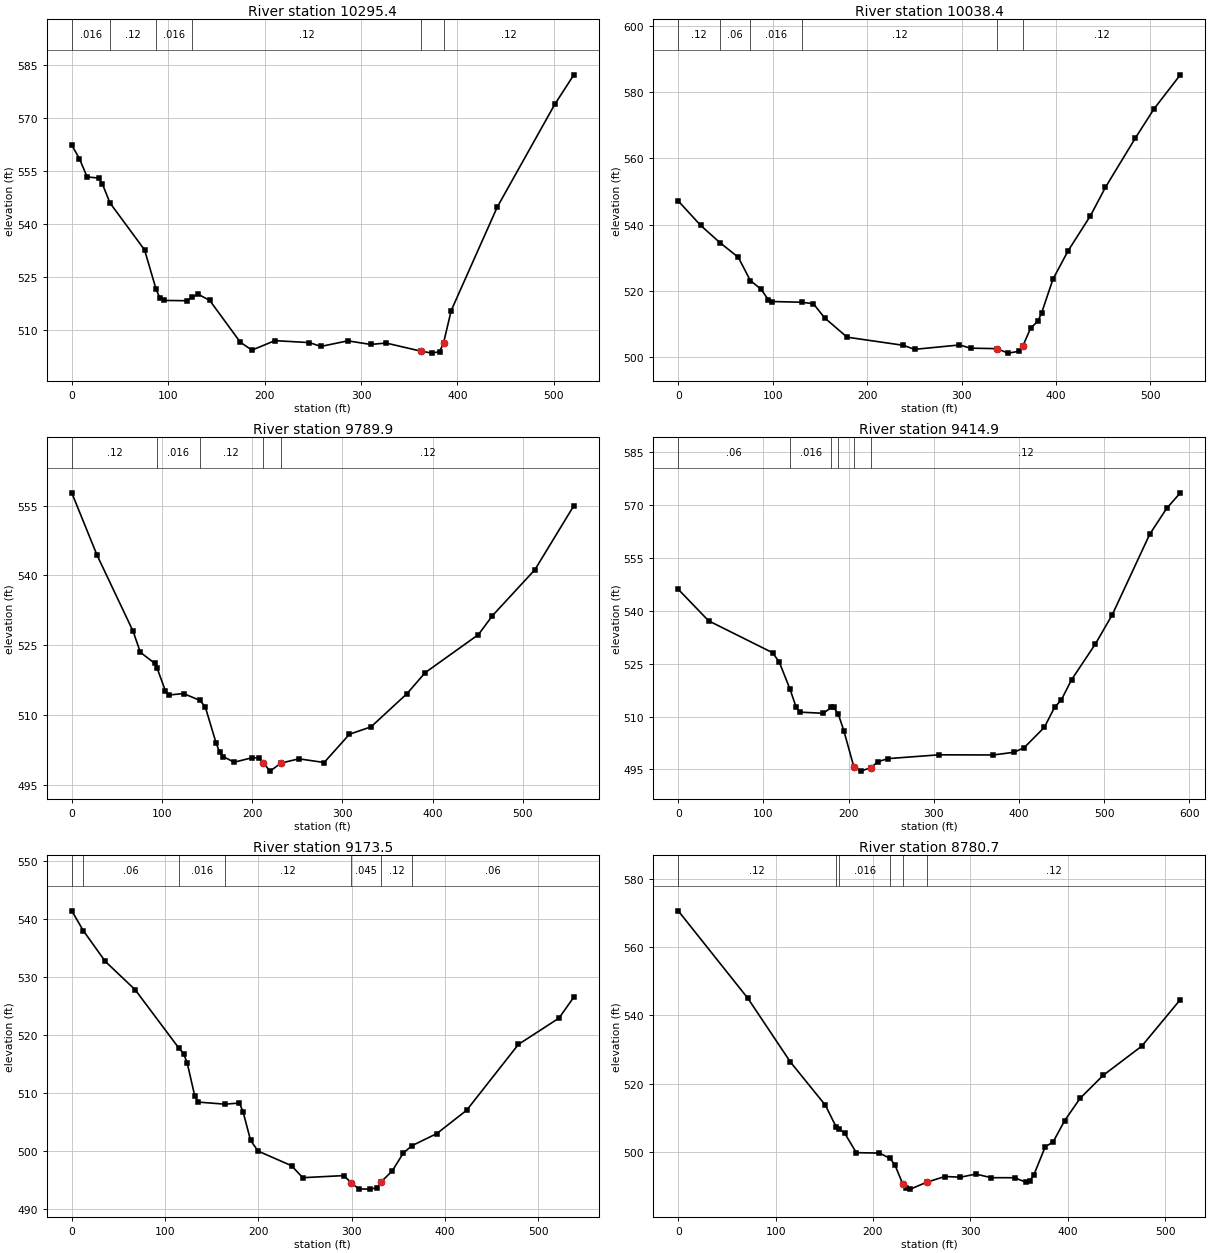
Type RM Length L Ch R = 1 ,10295.4 ,256.2,257,257.7
XS GIS Cut Line= 2
     2303250.728      403845.975     2303709.061      403598.579
#Sta/Elev= 30
       0  562.37       8  558.49    15.9  553.34    27.8  553.02    31.8  551.32
    39.6545.9835    75.5  532.66   87.42521.5416    91.4  518.99    95.4  518.34
   119.3  518.25  125.07519.2748   131.2  520.07   143.1  518.34   174.9  506.47
   186.9  504.25   210.7  506.94   246.5  506.38   258.4   505.3   286.3  506.88
   310.1  505.86     326  506.26   361.8  503.98   373.7   503.4   381.7  503.84
   385.7  506.37   393.6  515.48   441.3  544.77     501  573.91   520.8  582.28
#Mann= 6 ,-1 , 0
       0    .016       0    39.6     .12       0   87.42    .016       0
  125.07     .12       0   361.8    .045       0   385.7     .12       0
Bank Sta=361.8,385.7
XS Rating Curve= 0 ,0
Exp/Cntr=0.3,0.1

Type RM Length L Ch R = 1 ,10038.4 ,248.6,248.5,267.4
XS GIS Cut Line= 3
     2303404.374      404103.788     2303517.655        403986.6
     2303847.082      403821.235
#Sta/Elev= 30
       0  547.11    23.8  539.72      44 534.577    63.6   530.1   76.38523.0748
    87.5  520.53    95.4  517.32    99.4  516.77  130.91516.5378   143.1   516.1
     155  511.83   178.8     506   238.3  503.55   250.2  502.33   297.8  503.65
   309.6  502.69   337.4  502.54   349.3  501.19   361.2  501.76   365.1  503.48
     373  508.66     381  510.92   384.9  513.45   396.8  523.53   412.7  532.03
   436.5  542.67   452.3  551.22     484   566.1   503.8  574.92   531.6  585.18
#Mann= 6 ,-1 , 0
       0     .12       0      44     .06       0   76.38    .016       0
  130.91     .12       0   337.4    .045       0   365.1     .12       0
Bank Sta=337.4,365.1
XS Rating Curve= 0 ,0
Exp/Cntr=0.3,0.1

Type RM Length L Ch R = 1 ,9789.9  ,374.7,374.9,349.1
XS GIS Cut Line= 3
     2303465.572      404233.996      2303821.04       404042.59
     2303973.384      404029.569
#Sta/Elev= 30
       0  557.73      28  544.36      68  528.01      76  523.51    91.9  521.14
   94.64520.0851   103.9  515.18   107.9  514.34   123.9  514.65  141.87513.1945
   147.9  511.85   159.9   504.1   163.9  502.02   167.9  501.13   179.9  499.91
   199.9  500.87   207.9  500.83     212  499.85   219.8     498     232  499.73
   251.8  500.64   279.8  499.85   307.8  505.91   331.8  507.51   371.8  514.66
   391.7  519.12   450.8   527.3   466.4  531.37   513.5  541.25   556.6  554.97
#Mann= 5 ,-1 , 0
       0     .12       0   94.64    .016       0  141.87     .12       0
     212    .045       0     232     .12       0
Bank Sta=212,232
XS Rating Curve= 0 ,0
Exp/Cntr=0.3,0.1

Type RM Length L Ch R = 1 ,9414.9  ,240.2,241.4,241.3
XS GIS Cut Line= 3
     2303598.384      404470.975     2303728.592      404478.788
     2304097.082       404205.35
#Sta/Elev= 30
       0  546.13    35.6  537.18   110.7  528.12   118.6  525.46   131.3517.6967
   138.4  512.62   142.4  511.25   170.3  510.92  179.57512.5795   182.3   512.6
  187.78510.7446   194.3  506.03   206.2  495.65   214.2   494.5   226.2  495.49
   234.2  497.15   246.2  498.05     306  499.13   369.8  499.09   393.8  499.84
   405.8   501.1   429.7  506.93   441.7   512.6   449.6   514.7   461.6  520.43
   489.6  530.59   509.5  538.93   553.4  561.75   573.3   569.1   589.3  573.51
#Mann= 6 ,-1 , 0
       0     .06       0   131.3    .016       0  179.57     .06       0
  187.78     .12       0   206.2    .045       0   226.2     .12       0
Bank Sta=206.2,226.2
XS Rating Curve= 0 ,0
Exp/Cntr=0.3,0.1

Type RM Length L Ch R = 1 ,9173.5  ,385.7,392.8,396.5
XS GIS Cut Line= 3
     2303746.822      404723.579     2304093.176      404473.579
     2304203.853      404478.788
#Sta/Elev= 30
       0   541.4   12.34 537.986    35.9  532.69    67.9  527.81  114.54517.7974
   119.8  516.82   123.8  515.12   131.7  509.57   135.7  508.45   164.1 508.096
   179.6  508.29   183.6  506.76   191.6  501.86   199.6  500.02   235.5  497.49
   247.5  495.43   291.4  495.79   299.4  494.58   307.4   493.5   319.4  493.46
   327.4  493.72   331.3  494.69   343.3  496.57   355.3  499.68  364.45500.9366
   391.2  503.03   423.2  507.06   478.6  518.39   522.1  522.92     538  526.54
#Mann= 7 ,-1 , 0
       0     .12       0   12.34     .06       0  114.54    .016       0
   164.1     .12       0   299.4    .045       0   331.3     .12       0
  364.45     .06       0
Bank Sta=299.4,331.3
XS Rating Curve= 0 ,0
Exp/Cntr=0.3,0.1

Type RM Length L Ch R = 1 ,8780.7  ,223.2,221.6,219.9
XS GIS Cut Line= 3
     2303886.144      405020.454     2304020.259      404901.965
     2304326.249       404761.34
#Sta/Elev= 30
       0  570.64    71.6  544.97   115.3   526.3   151.1  513.69  162.03507.4127
  165.12506.7374     171  505.45   182.9  499.77   206.7  499.64  217.56 498.087
   222.5  496.22   230.5  490.67   234.4  489.38   238.4  489.08   255.6  491.15
     274  492.78   289.9  492.58   305.7  493.49   321.6  492.43   345.4  492.42
   357.2  491.11   361.2   491.6   365.2  493.22     377  501.52     385  502.87
   396.9  509.15   412.7  515.67   436.5  522.44   476.1  530.99   515.7  544.61
#Mann= 6 ,-1 , 0
       0     .12       0  162.03     .06       0  165.12    .016       0
  217.56     .12       0   230.5    .045       0   255.6     .12       0
Bank Sta=230.5,255.6
XS Rating Curve= 0 ,0
Exp/Cntr=0.3,0.1

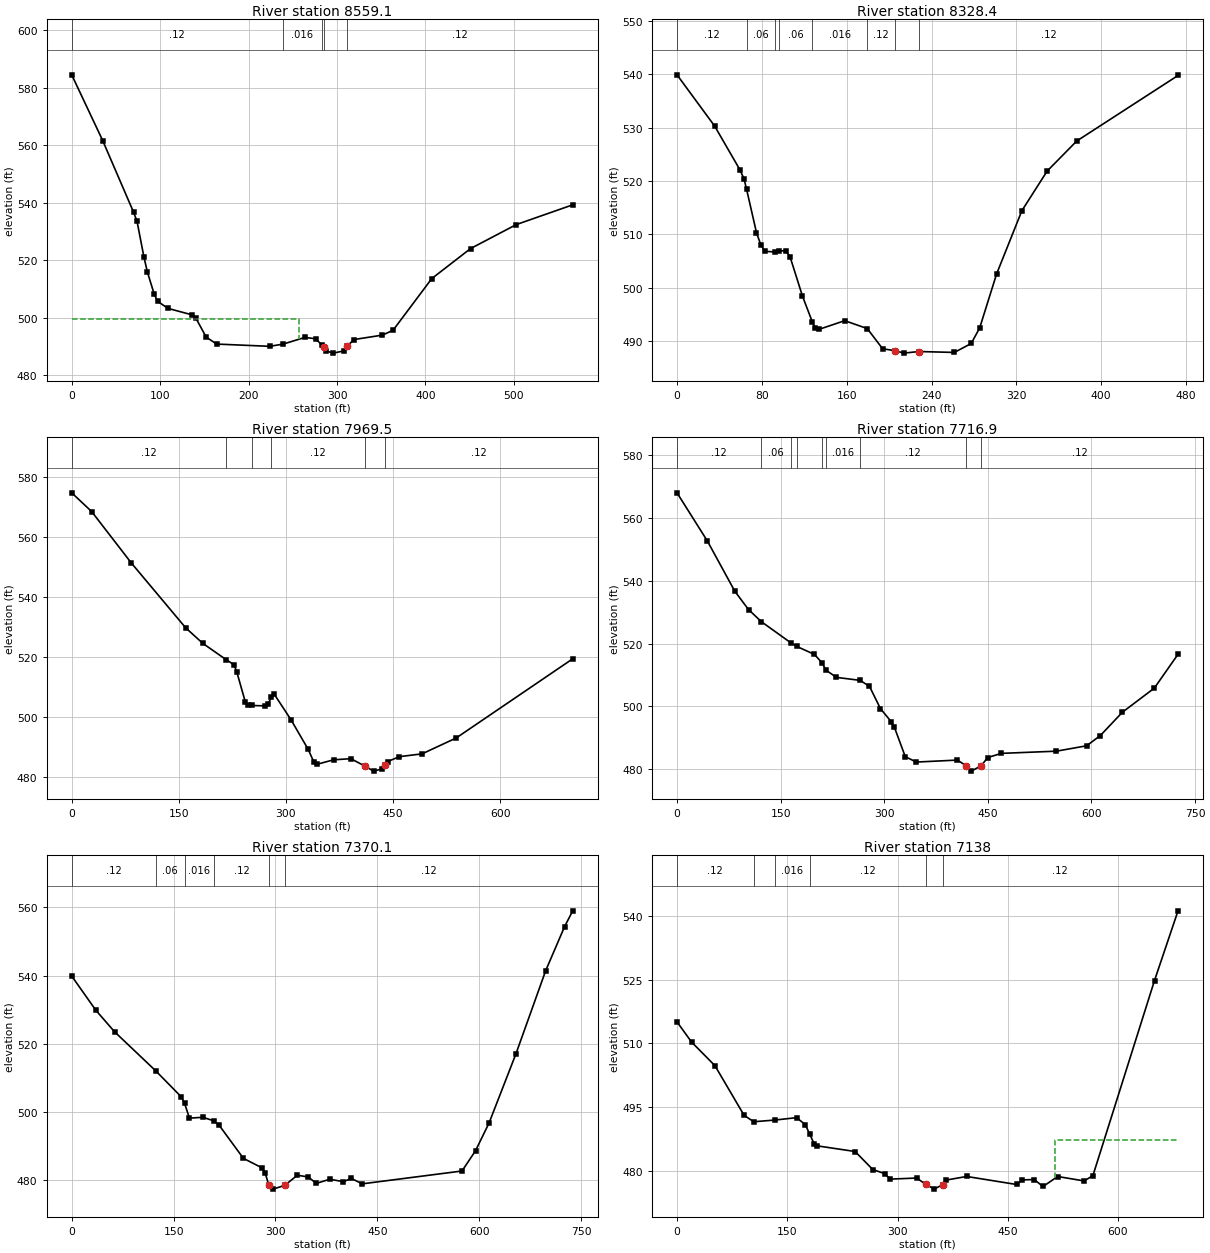
Type RM Length L Ch R = 1 ,8559.1  ,246.7,230.7,215.7
XS GIS Cut Line= 4
     2303919.999      405171.496     2304052.811      405141.548
     2304314.802      404997.511      2304446.04      404990.506
#Sta/Elev= 30
       0  584.55      35   561.7      70  536.72    73.9  533.53    81.7  521.11
    85.6  515.91    93.4  508.14    97.2  505.73   108.9  503.28   136.2  501.03
   140.1  500.07   152.1  493.28     164  490.87   223.8  490.09   238.9490.8448
   263.7  493.19   275.7  492.72  282.56490.6702   284.8   489.7   287.6   488.5
   295.6  487.72   307.6  488.48   311.6  490.24   319.5  492.46   351.4  493.99
   363.4  495.67   407.2  513.66     451  524.09   502.8  532.45   566.6  539.32
#Mann= 5 ,-1 , 0
       0     .12       0   238.9    .016       0  282.56     .12       0
   284.8    .045       0   311.6     .12       0
#XS Ineff= 2 , 0
          256.48  499.59
Permanent Ineff=
       F       F
Bank Sta=284.8,311.6
XS Rating Curve= 0 ,0
Exp/Cntr=0.3,0.1

Type RM Length L Ch R = 1 ,8328.4  ,344,358.9,369.4
XS GIS Cut Line= 3
     2304245.519      405439.725     2304293.697      405331.652
     2304452.551      405015.246
#Sta/Elev= 30
       0  539.91    35.5  530.29    59.2  522.13    63.1  520.44   65.53 518.496
    74.9  510.32    78.9  508.06    82.8   506.8   92.08  506.67   96.07506.9092
   102.6  506.86   106.5  505.82   118.3  498.38  127.48493.6032   130.3  492.44
   134.2  492.17   158.1  493.78  179.38492.2964   193.9   488.5   205.8  488.15
   213.8  487.69   228.2  487.99   261.5  487.82   277.4   489.5   285.4  492.43
   301.3  502.53   325.2  514.43     349  521.85   376.9  527.49   472.4  539.79
#Mann= 8 ,-1 , 0
       0     .12       0   65.53     .06       0   92.08     .08       0
   96.07     .06       0  127.48    .016       0  179.38     .12       0
   205.8    .045       0   228.2     .12       0
Bank Sta=205.8,228.2
XS Rating Curve= 0 ,0
Exp/Cntr=0.3,0.1

Type RM Length L Ch R = 1 ,7969.5  ,253.2,252.6,252.1
XS GIS Cut Line= 3
     2304257.142      405680.156     2304729.894      405347.277
     2304793.697      405241.808
#Sta/Elev= 30
       0  574.78    27.9  568.54    83.7  551.31   159.5  529.77   183.4  524.59
  216.25 519.127   227.3  517.43   231.3   514.9   243.2  504.91   247.2  503.86
  251.94503.8485   271.2  503.71   275.1  504.38  279.42 506.584   283.1  507.78
     307   499.1     331  489.24   338.9  485.06   342.9   484.2   366.8  485.73
   390.8   486.1   410.7   483.6   422.7  481.95   434.6   482.7   439.3  484.12
   442.6  485.16   458.6  486.77   490.5  487.71   538.3     493   701.5  519.42
#Mann= 6 ,-1 , 0
       0     .12       0  216.25     .06       0  251.94    .016       0
  279.42     .12       0   410.7    .045       0   439.3     .12       0
Bank Sta=410.7,439.3
XS Rating Curve= 0 ,0
Exp/Cntr=0.3,0.1

Type RM Length L Ch R = 1 ,7716.9  ,346.5,346.7,344.9
XS GIS Cut Line= 3
     2304416.344      405888.291     2304944.738      405498.319
     2304982.499      405441.027
#Sta/Elev= 30
       0   568.1    43.8   552.8    83.6  536.76   103.5   530.9  122.01527.0488
  164.85520.2827  173.43519.1346     199  516.59  209.67513.9855  215.72511.5789
   230.8  509.28  264.83508.3362   278.6  506.44   294.5  499.31   310.4  495.09
   314.4  493.56   330.4  484.03   346.3  482.29     406  482.92   417.9  481.19
   425.9   479.4   440.3  481.09   449.8  483.73   469.6  485.06   549.3  485.76
     593  487.48   612.9  490.75   644.8  498.18     691  505.86   725.3  516.65
#Mann= 9 ,-1 , 0
       0     .12       0  122.01     .06       0  164.85     .08       0
  173.43     .06       0  209.67     .12       0  215.72    .016       0
  264.83     .12       0   417.9    .045       0   440.3     .12       0
Bank Sta=417.9,440.3
XS Rating Curve= 0 ,0
Exp/Cntr=0.3,0.1

Type RM Length L Ch R = 1 ,7370.1  ,230.3,232.1,232.4
XS GIS Cut Line= 3
     2304625.728      406088.163     2304784.582      406029.569
     2305233.149      405680.715
#Sta/Elev= 30
       0  539.87    35.4  529.87      63  523.54  124.08 511.988   161.4  504.41
  166.17502.5182   173.3  498.19   193.2  498.43  209.66497.3623     217  496.11
   252.8  486.38   280.6  483.56   284.6  482.23  290.27  478.45   296.5  477.36
   313.7  478.47   332.2  481.43   348.1  480.94   360.1  479.04   379.9  480.26
   399.8  479.55   411.7   480.5   427.6  478.91   574.6  482.68   594.5  488.63
   614.4  496.76   654.1  517.11   697.8  541.46   725.6  554.38   737.6  559.01
#Mann= 6 ,-1 , 0
       0     .12       0  124.08     .06       0  166.17    .016       0
  209.66     .12       0  290.27    .045       0   313.7     .12       0
Bank Sta=290.27,313.7
XS Rating Curve= 0 ,0
Exp/Cntr=0.3,0.1

Type RM Length L Ch R = 1 ,7138    ,328,332.4,335
XS GIS Cut Line= 3
     2304753.332      406172.798     2304931.717      406176.704
     2305337.967      405879.829
#Sta/Elev= 30
       0  515.04    19.8   510.3    51.6  504.73    91.2  493.06  104.31491.5262
  133.85491.9383   162.6  492.49   174.5  490.86  180.26488.7079   186.4   486.4
   190.4  485.86   242.3  484.52   266.3  480.28   282.3  479.32   290.2  478.02
   326.2  478.27   338.2   476.8   350.1  475.66  361.36  476.74   366.1  477.79
   394.1  478.64     462  476.75   469.9  477.83   485.9  477.92   497.9  476.28
   517.9  478.63   553.8  477.59   565.8  478.84   649.6  524.79   681.6   541.2
#Mann= 6 ,-1 , 0
       0     .12       0  104.31     .06       0  133.85    .016       0
  180.26     .12       0   338.2    .045       0  361.36     .12       0
#XS Ineff= 2 , 0
                          514.89          487.24
Permanent Ineff=
       F       F
Bank Sta=338.2,361.36
XS Rating Curve= 0 ,0
Exp/Cntr=0.3,0.1