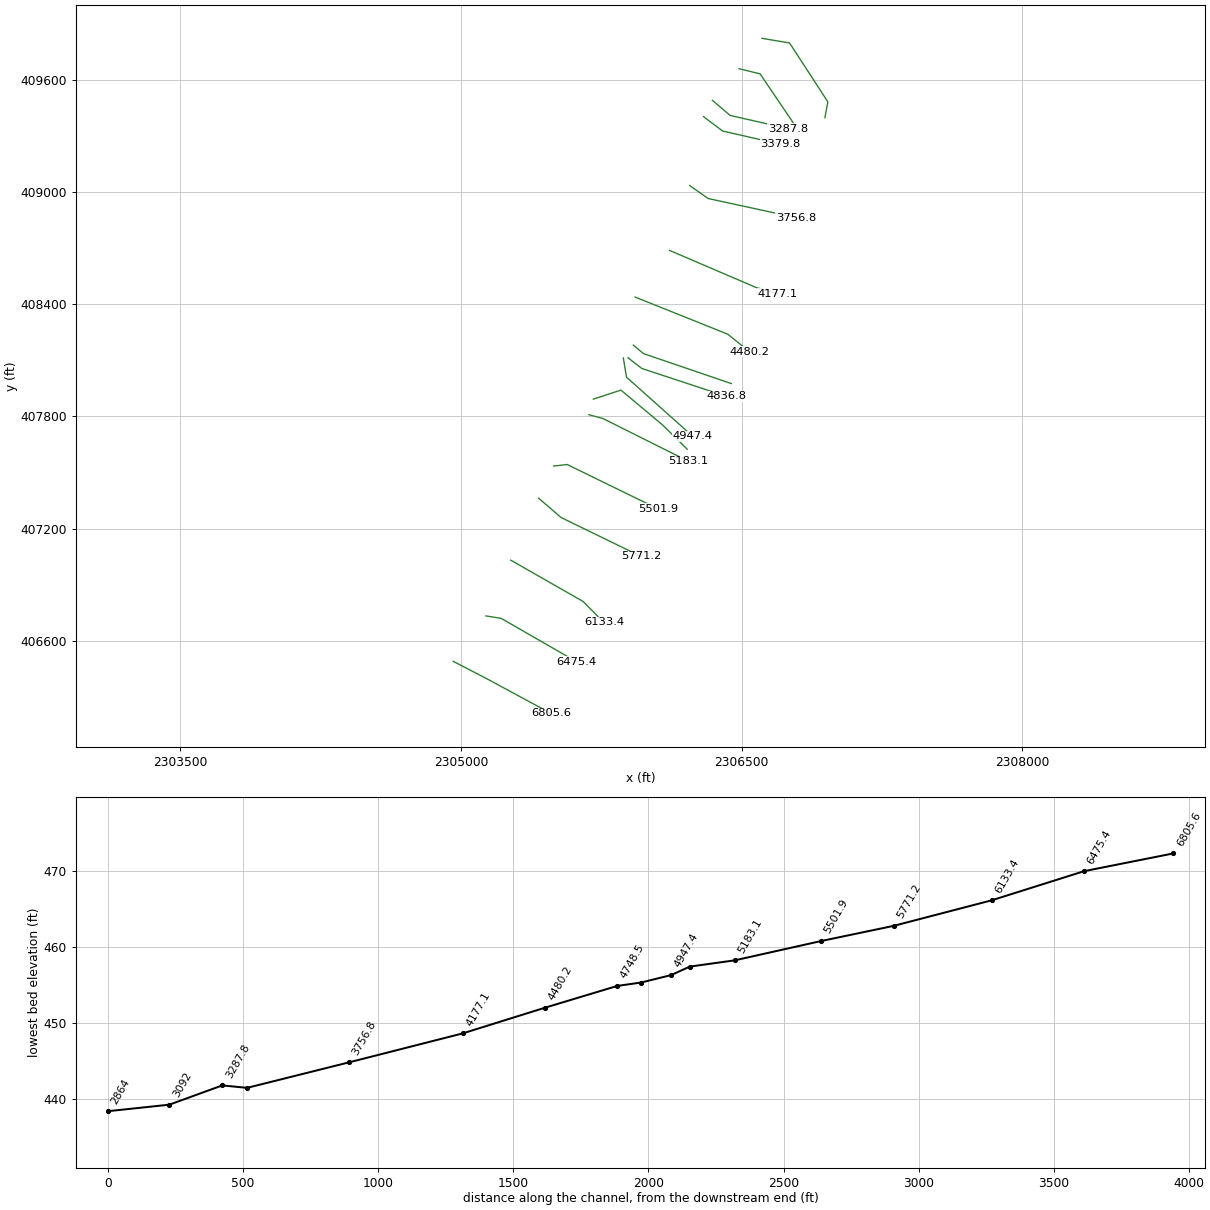
HEC-RAS study LONGHOLLOW.prj: LONGHOLLOW

--- LONGHOLLOW.g01 (geometry) --- (continued)

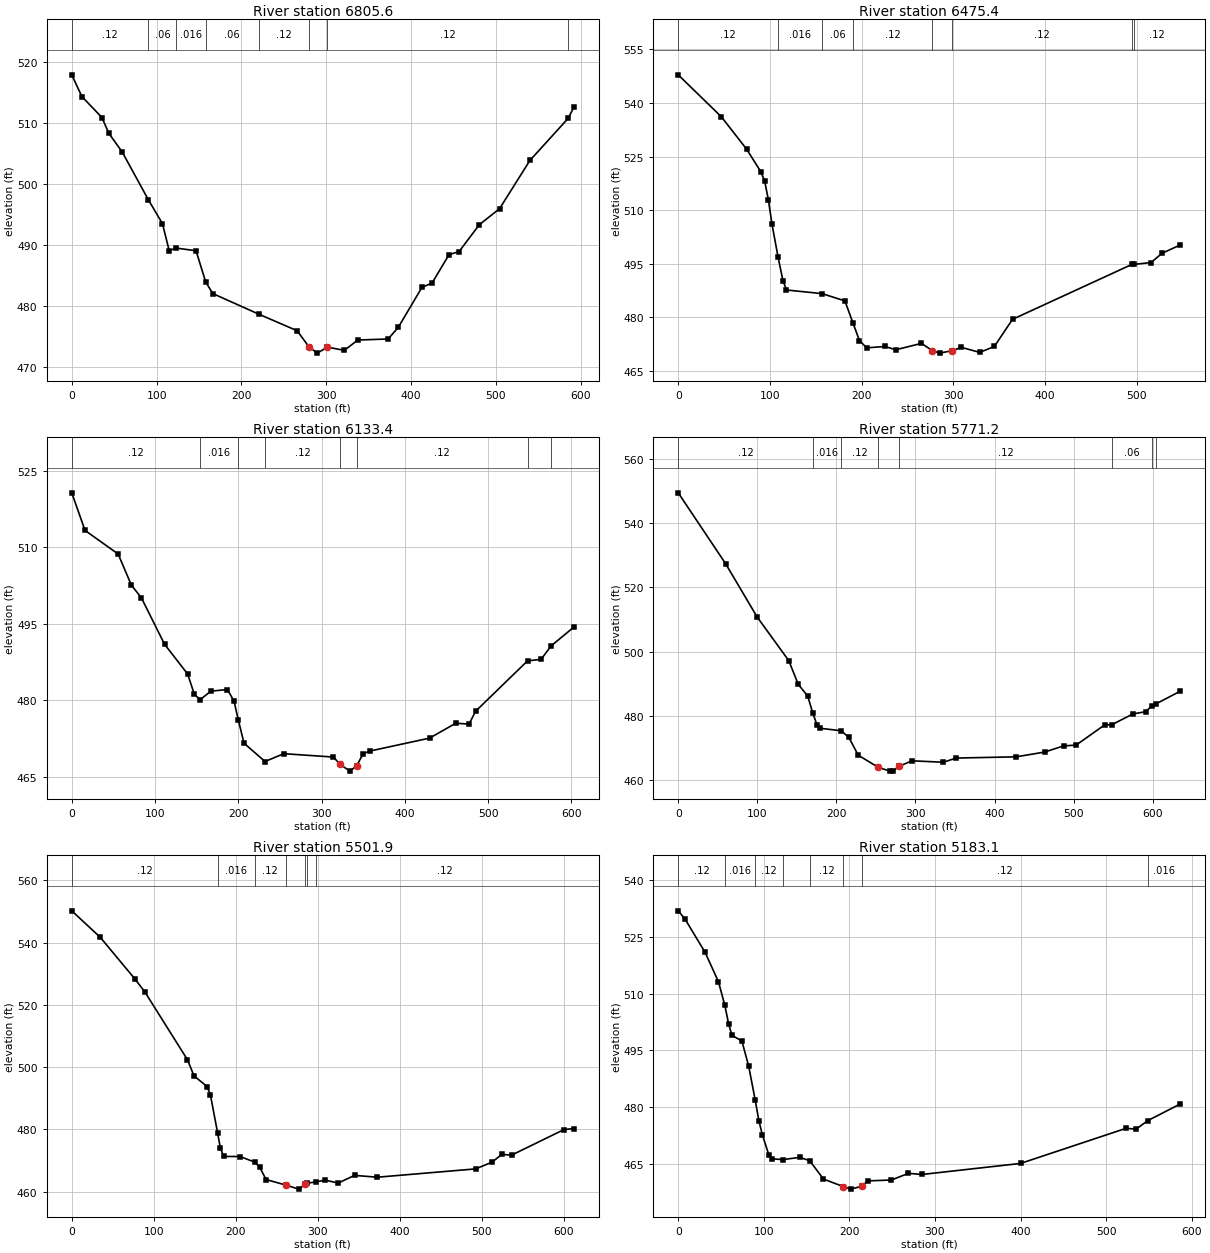
Type RM Length L Ch R = 1 ,6805.6  ,330.2,330.2,329.6
XS GIS Cut Line= 3
     2304959.061      406489.204     2305134.842      406398.058
     2305481.197      406210.558
#Sta/Elev= 30
       0  517.95    11.9  514.39    35.6  510.94    43.6  508.37    59.4   505.3
   90.39497.4186   106.9  493.53   114.8  489.12  123.35489.5153   146.5  489.08
  157.95483.9311   166.3  482.05  220.57478.6697   265.6  475.96  279.61  473.32
   289.5  472.28   301.4  473.27   321.3  472.73   337.2  474.43     373   474.6
     385  476.53   412.8  483.06   424.8  483.79   444.7  488.43   456.6  488.95
   480.5  493.36   504.3  495.98   540.1   503.9  585.31510.8255   591.9  512.64
#Mann= 8 ,-1 , 0
       0     .12       0   90.39     .06       0  123.35    .016       0
  157.95     .06       0  220.57     .12       0  279.61    .045       0
   301.4     .12       0  585.31     .06       0
Bank Sta=279.61,301.4
XS Rating Curve= 0 ,0
Exp/Cntr=0.3,0.1

Type RM Length L Ch R = 1 ,6475.4  ,340.2,342.1,339.3
XS GIS Cut Line= 3
     2305133.469      406732.208     2305214.817      406719.396
     2305617.987      406487.086
#Sta/Elev= 30
       0  547.89    47.1  536.12    74.5   527.1    90.3  520.67    94.3   518.1
    98.3  512.96   102.2  506.16  108.94496.7926   114.2  490.28   118.1  487.63
  156.88486.6149   181.8  484.58  190.63478.3809   197.7  473.46   205.6  471.43
   225.5  471.81   237.4  470.89   265.3  472.68   277.2  470.65   285.2  469.95
  299.04  470.65     309  471.56   328.9  470.15   344.8  471.81   364.7  479.42
  494.79494.7837  497.07494.8036   515.8  495.32   527.8  497.92   547.7  500.25
#Mann= 8 ,-1 , 0
       0     .12       0  108.94    .016       0  156.88     .06       0
  190.63     .12       0   277.2    .045       0  299.04     .12       0
  494.79     .06       0  497.07     .12       0
Bank Sta=277.2,299.04
XS Rating Curve= 0 ,0
Exp/Cntr=0.3,0.1

Type RM Length L Ch R = 1 ,6133.4  ,359.4,362.2,363
XS GIS Cut Line= 3
     2305266.353      407030.871     2305653.072      406809.517
     2305763.749      406697.538
#Sta/Elev= 30
       0  520.69    15.9  513.32    55.7  508.69    71.6  502.58    83.6  500.11
   111.4     491   139.2  485.16   147.2  481.18  154.21480.1384   167.1   481.8
     187  482.12   194.9  479.82  200.01476.1576   206.9  471.59  232.12468.0062
   254.6  469.54   314.3  468.88   322.3  467.42   334.2  466.12   342.2  467.19
   350.1  469.56   358.1  470.06   429.7  472.59   461.3  475.52   477.1  475.33
     485  477.86  547.37487.7403   563.7  488.05  575.73490.6765     603  494.36
#Mann= 8 ,-1 , 0
       0     .12       0  154.21    .016       0  200.01     .06       0
  232.12     .12       0   322.3    .045       0   342.2     .12       0
  547.37     .06       0  575.73     .12       0
Bank Sta=322.3,342.2
XS Rating Curve= 0 ,0
Exp/Cntr=0.3,0.1

Type RM Length L Ch R = 1 ,5771.2  ,269.3,269.2,269.2
XS GIS Cut Line= 3
      2305414.79      407362.902     2305535.884      407258.735
     2305962.967      407050.402
#Sta/Elev= 30
       0  549.41    59.9  527.35    99.8  510.74   139.8  497.16   151.8  489.77
   163.7  486.15  170.07480.9166   175.7  477.01   179.7   476.1  205.76475.3557
   215.6  473.34   227.6  467.73  252.98  463.95   267.6  462.77   271.5  462.77
   279.5   464.3   295.5  465.98   335.4  465.54   351.4  466.84   427.3  467.22
   463.2   468.7   487.2  470.62   503.1  470.87   539.1  477.14  548.39477.2303
     575  480.58     591  481.26  598.65 482.999  604.09483.7018   634.9  487.66
#Mann= 8 ,-1 , 0
       0     .12       0  170.07    .016       0  205.76     .12       0
  252.98    .045       0   279.5     .12       0  548.39     .06       0
  598.65     .08       0  604.09    .016       0
Bank Sta=252.98,279.5
XS Rating Curve= 0 ,0
Exp/Cntr=0.3,0.1

Type RM Length L Ch R = 1 ,5501.9  ,318.2,318.8,317.9
XS GIS Cut Line= 3
     2305495.519      407534.777     2305568.436       407542.59
     2306052.811       407305.61
#Sta/Elev= 30
       0  550.18    34.7  541.69    77.3  528.21    89.3  524.08   141.2  502.32
   149.2  497.13   165.2  493.72   169.2  491.01   177.9 478.882   181.2  474.13
   185.2  471.26   205.2  471.25  223.17469.4605   229.1  467.89   237.1  463.85
   261.1  462.08     277  460.77     285  462.33   287.6 462.715  297.74 463.054
     309  463.68     325  462.72     345  465.18   372.9   464.6   492.7  467.27
   512.7  469.42   524.7  471.92   536.7   471.7   600.6  479.91   612.6  480.24
#Mann= 7 ,-1 , 0
       0     .12       0   177.9    .016       0  223.17     .12       0
   261.1    .045       0     285     .12       0   287.6     .06       0
  297.74     .12       0
Bank Sta=261.1,285
XS Rating Curve= 0 ,0
Exp/Cntr=0.3,0.1

Type RM Length L Ch R = 1 ,5183.1  ,171.6,166.1,159.6
XS GIS Cut Line= 3
     2305684.322      407809.517     2305759.842      407788.683
     2306214.269      407560.819
#Sta/Elev= 30
       0  531.91     7.8  529.77    31.3  520.96      47  513.14   54.48506.8802
    58.8  502.07    62.7  498.97    74.4  497.43    82.3  490.81   89.87481.8932
    94.2   476.4    98.2  472.68   106.1  467.15   110.1  466.24  122.62466.0634
   141.9  466.65  153.62465.7711   169.7   460.9   192.7  458.93   201.5  458.24
  214.52  458.99   221.3  460.42   249.1  460.65     269  462.42   284.9  462.12
     400  465.04   523.2  474.33   535.1  474.13  548.55476.3584   586.7  480.79
#Mann= 8 ,-1 , 0
       0     .12       0   54.48    .016       0   89.87     .12       0
  122.62    .016       0  153.62     .12       0   192.7    .045       0
  214.52     .12       0  548.55    .016       0
Bank Sta=192.7,214.52
XS Rating Curve= 0 ,0
Exp/Cntr=0.3,0.1

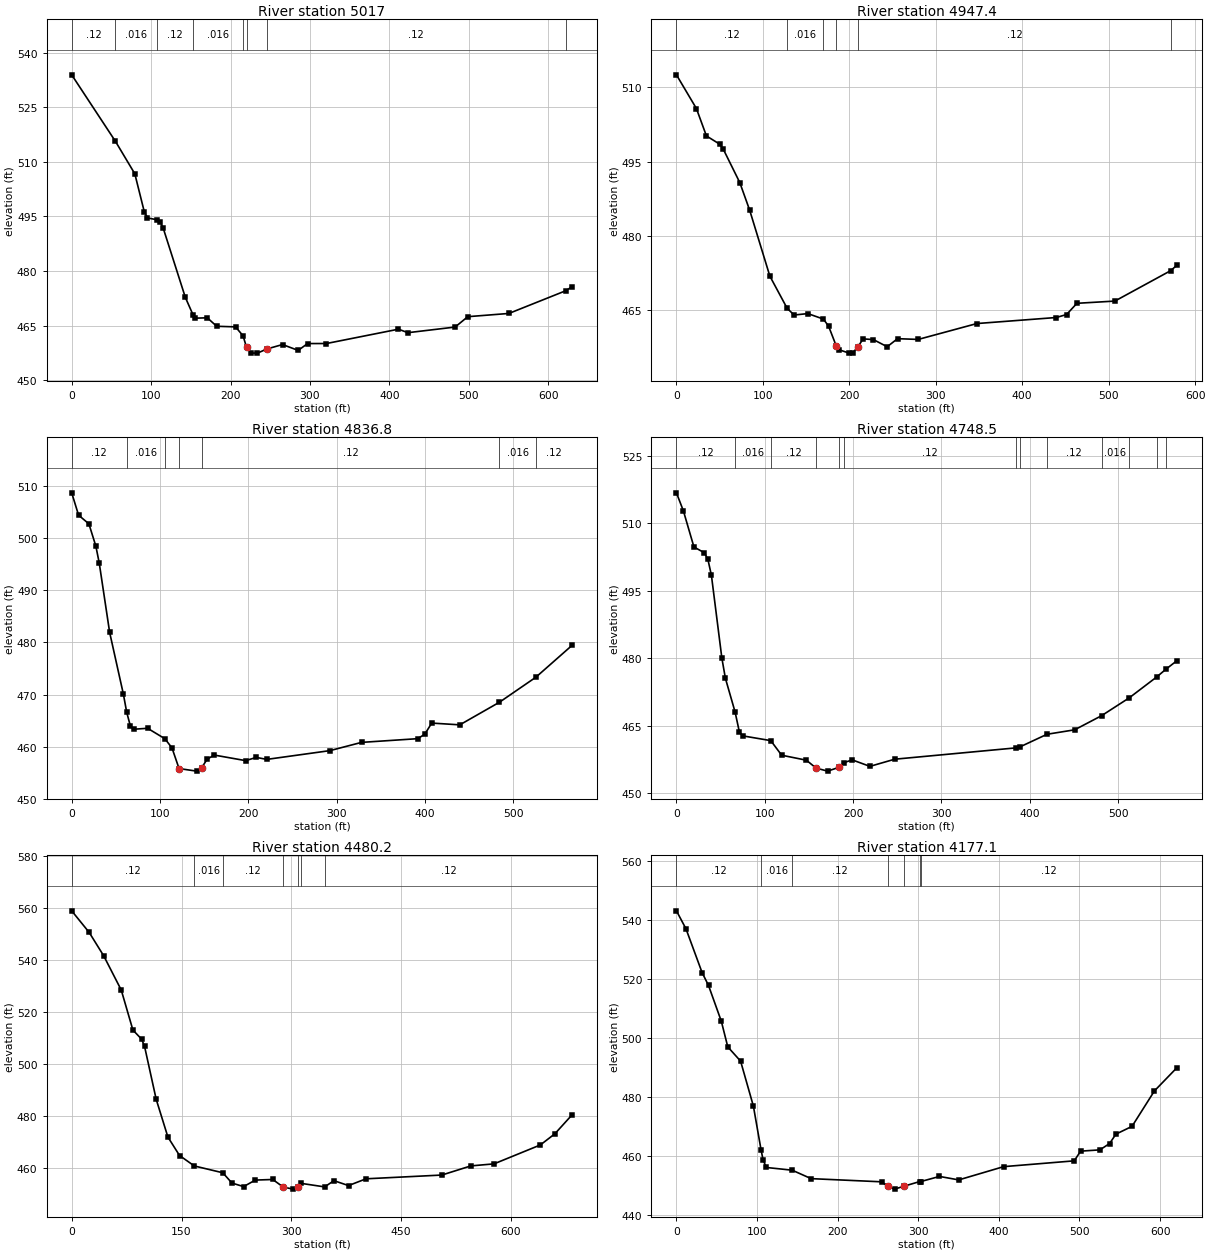
Type RM Length L Ch R = 1 ,5017    ,70.4,69.6,69.1
XS GIS Cut Line= 4
     2305707.759       407892.85     2305855.011      407941.166
     2306078.853      407753.527     2306209.061      407624.621
#Sta/Elev= 30
       0  533.93   55.16515.6202    79.5  506.72    91.4   496.3    95.4  494.59
  106.93494.1081   111.3  493.57   115.2  491.82   143.1  472.75  152.93467.8891
     155  467.03   170.8  467.13   182.6   464.8   206.3  464.64  215.77462.1992
   220.2  459.02     226  457.44   233.9  457.42   245.8  458.56   265.5  459.78
   285.2  458.17   297.1  460.05   320.8  460.06   411.5     464   423.4  463.04
   482.9  464.59   498.8  467.44   550.6  468.33  622.25474.5772   630.3  475.71
#Mann= 8 ,-1 , 0
       0     .12       0   55.16    .016       0  106.93     .12       0
  152.93    .016       0  215.77     .12       0   220.2    .045       0
   245.8     .12       0  622.25    .016       0
Bank Sta=220.2,245.8
XS Rating Curve= 0 ,0
Exp/Cntr=0.3,0.1

Type RM Length L Ch R = 1 ,4947.4  ,100.2,110.6,121
XS GIS Cut Line= 3
     2305867.915      408112.902     2305884.959      408010.177
     2306239.009      407693.631
#Sta/Elev= 30
       0  512.55    23.1  505.74    34.7   500.2    50.1  498.53      54  497.59
    73.3  490.77    84.8  485.15   108.1  471.85  127.99 465.386   136.1     464
     152  464.29     170 463.185     176  461.75     185   457.7   187.9  456.99
   199.9   456.3   203.9  456.35  210.19  457.63   215.9  459.18   227.8  459.04
   243.8  457.59   255.8  459.22   279.7  459.07   347.6  462.28   439.4   463.5
   451.3   464.1   463.3  466.37   507.2  466.82  571.73472.9662     579  474.07
#Mann= 6 ,-1 , 0
       0     .12       0  127.99    .016       0     170     .12       0
     185    .045       0  210.19     .12       0  571.73    .016       0
Bank Sta=185,210.19
XS Rating Curve= 0 ,0
Exp/Cntr=0.3,0.1

Type RM Length L Ch R = 1 ,4836.8  ,86.6,88.3,88.7
XS GIS Cut Line= 3
     2305892.655      408114.204     2305966.874      408056.913
     2306416.092      407908.475
#Sta/Elev= 30
       0  508.67     7.8  504.39    19.5  502.72    27.4  498.43    31.2  495.22
      43  481.91    58.6  470.04   62.32466.6062    66.4  464.02    70.3  463.36
      86  463.54  105.53461.5438   113.6  459.78   121.6  455.82   141.5  455.33
  147.25  455.99   153.4  457.61   161.4  458.41   197.1  457.34     209  457.96
     221  457.58   292.5  459.26   328.3  460.84   391.9  461.55   399.9   462.4
   407.8  464.54   439.6   464.2  484.55468.5408  525.74473.3262   566.9  479.46
#Mann= 7 ,-1 , 0
       0     .12       0   62.32    .016       0  105.53     .12       0
   121.6    .045       0  147.25     .12       0  484.55    .016       0
  525.74     .12       0
Bank Sta=121.6,147.25
XS Rating Curve= 0 ,0
Exp/Cntr=0.3,0.1

Type RM Length L Ch R = 1 ,4748.5  ,271.2,268.3,265.8
XS GIS Cut Line= 3
     2305921.301      408181.913     2305975.988       408136.34
     2306444.738      407976.183
#Sta/Elev= 30
       0  516.79     7.9  512.76    19.8  504.75    31.6  503.45    35.6     502
    39.6  498.43    51.4  480.05    55.4  475.55   66.41468.0124    71.2  463.63
    75.2  462.72  106.76461.6679   119.1  458.42   147.1  457.31  158.03  455.56
   171.1  454.88   184.5455.7612  189.78456.7757     199  457.38     219  455.94
     247  457.53  384.28460.0518  388.44460.2384  419.46463.0809   450.7  464.07
  481.21467.2133  512.53471.1851  543.55475.8211  554.28477.5884   566.5  479.45
#Mann= 13 ,-1 , 0
       0     .12       0   66.41    .016       0  106.76     .12       0
  158.03    .045       0   184.5     .06       0  189.78     .12       0
  384.28    .016       0  388.44     .08       0  419.46     .12       0
  481.21    .016       0  512.53     .08       0  543.55     .12       0
  554.28    .016       0
Bank Sta=158.03,184.5
XS Rating Curve= 0 ,0
Exp/Cntr=0.3,0.1

Type RM Length L Ch R = 1 ,4480.2  ,303.3,303.1,301.7
XS GIS Cut Line= 3
     2305930.741      408439.334     2306425.653      408240.512
      2306542.72      408146.366
#Sta/Elev= 30
       0  558.78    23.9  550.49    43.8  541.48    67.7  528.38    83.6  513.04
    95.5  509.55    99.5   506.8   115.4  486.48   131.4  471.99   147.3  464.91
  167.49460.8958  206.35458.2897   218.9  454.34   234.8  452.98   250.8  455.48
   274.6  455.71     289  452.79   302.5  452.01     309  452.72  313.86   454.2
  345.47452.8655   358.2  455.25   378.1  453.37     402  455.97   505.5  457.41
   545.2  460.92   576.8   461.7   640.1  468.96   659.9  473.23   683.6  480.57
#Mann= 7 ,-1 , 0
       0     .12       0  167.49    .016       0  206.35     .12       0
     289    .045       0     309     .12       0  313.86     .06       0
  345.47     .12       0
Bank Sta=289,309
XS Rating Curve= 0 ,0
Exp/Cntr=0.3,0.1

Type RM Length L Ch R = 1 ,4177.1  ,412.4,420.3,424.6
XS GIS Cut Line= 3
     2306115.203        408688.9     2306575.923      408490.984
     2306690.506       408457.13
#Sta/Elev= 30
       0   543.1    11.9  536.96    31.8  522.16    39.8  517.77    55.7  505.61
    63.7  496.93    79.6  492.09    95.5  476.78  104.94462.0431   107.4   458.7
   111.4     456  143.55455.0805   167.1  452.21   254.7  451.13   261.9  449.61
   270.6  448.65   281.9  449.61   301.6451.1995   302.9451.2037   326.3  452.96
   350.2  451.78   405.9  456.28   493.5  458.25   501.4  461.54   525.3  461.97
   537.3  464.11   545.2  467.31   565.2  469.96     593  481.99   620.9  489.87
#Mann= 7 ,-1 , 0
       0     .12       0  104.94    .016       0  143.55     .12       0
   261.9    .045       0   281.9     .12       0   301.6     .06       0
   302.9     .12       0
Bank Sta=261.9,281.9
XS Rating Curve= 0 ,0
Exp/Cntr=0.3,0.1

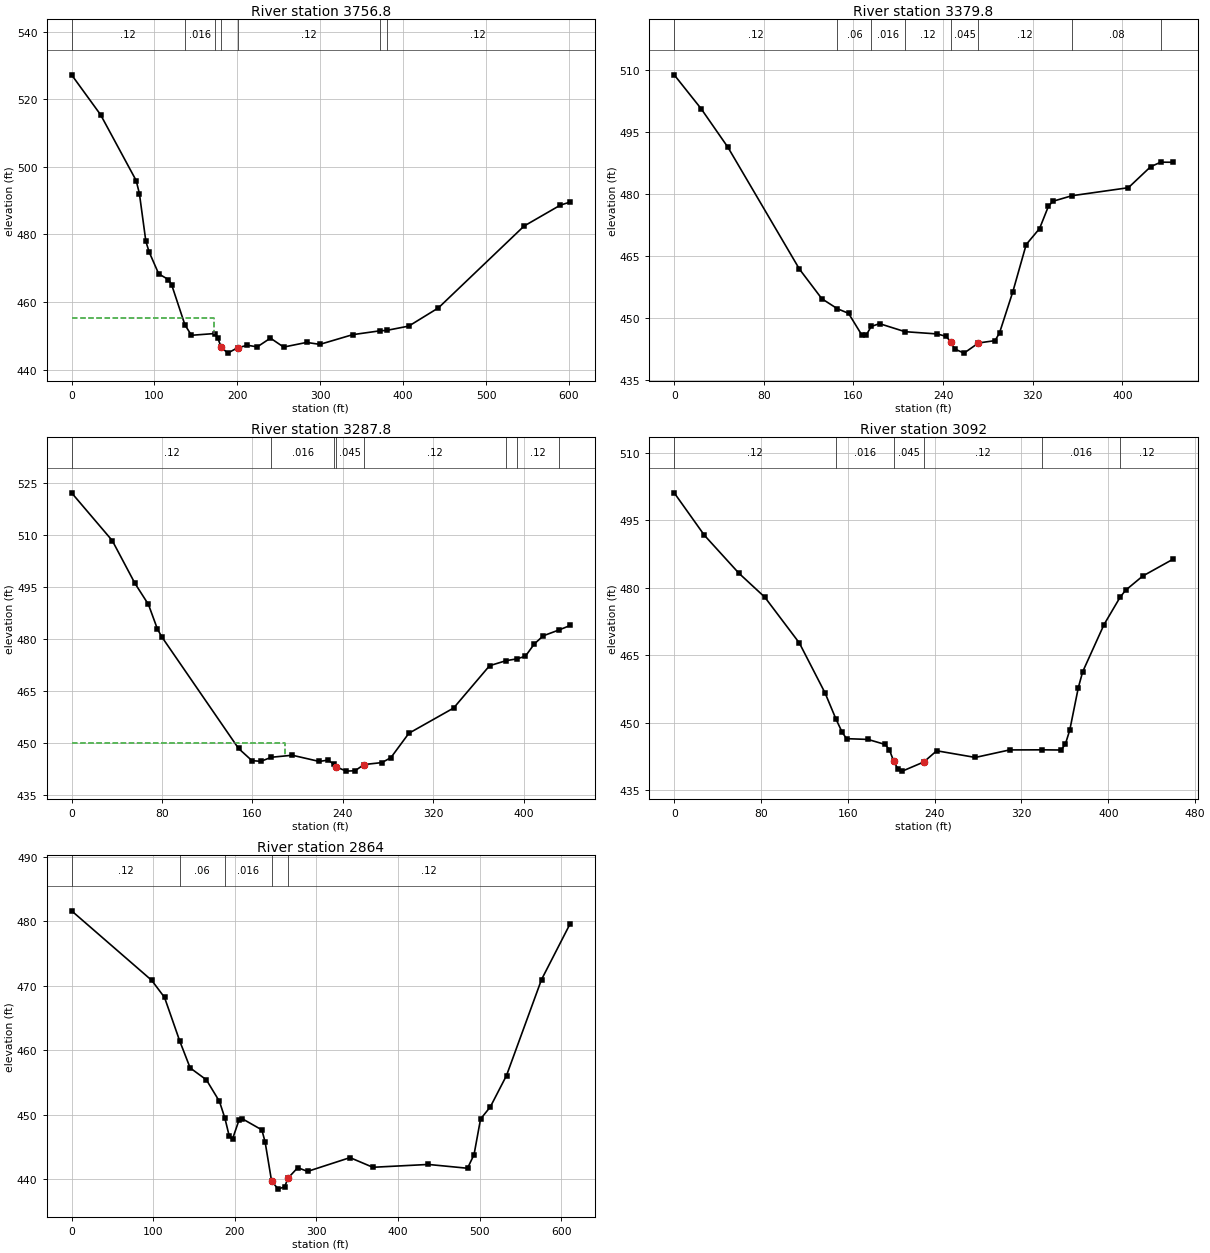
Type RM Length L Ch R = 1 ,3756.8  ,376.8,377.1,376.2
XS GIS Cut Line= 3
     2306222.624      409036.123     2306321.366      408966.678
     2306791.201      408864.682
#Sta/Elev= 30
       0  527.22      35   515.4    77.9  495.93    81.8  492.08    89.6  477.93
    93.5  474.82   105.1  468.31   116.8  466.63   120.7   465.1  136.69 453.233
   144.6  450.13  172.71450.6511   176.3  449.39   180.3  446.67   188.3  444.85
   200.2  446.42   212.1  447.18     224   446.7   239.9  449.29   255.8  446.64
   283.6  448.02   299.5  447.44   339.2  450.32  371.69451.4417  379.99451.5749
   406.8  452.85   442.6  458.25   545.9  482.46   589.6  488.64   601.5  489.57
#Mann= 7 ,-1 , 0
       0     .12       0  136.69    .016       0  172.71     .12       0
   180.3    .045       0   200.2     .12       0  371.69     .06       0
  379.99     .12       0
#XS Ineff= 2 , 0
          171.63  455.31
Permanent Ineff=
       F       F
Bank Sta=180.3,200.2
XS Rating Curve= 0 ,0
Exp/Cntr=0.3,0.1

Type RM Length L Ch R = 1 ,3379.8  ,92.3,92,92.6
XS GIS Cut Line= 3
     2306296.409      409405.046     2306398.406      409328.006
     2306707.651      409257.477
#Sta/Elev= 30
       0  508.73      24  500.56    47.9  491.25   111.8  461.79   131.8  454.64
  145.71452.2135   155.6  451.12   167.5  445.86   171.4  445.86  175.88447.9472
   183.3  448.62  206.04446.6805   234.9  446.13   242.8  445.54   246.8  444.21
   250.7  442.46   258.7   441.5   271.6  443.95   286.4  444.52   290.4   446.4
   302.3  456.36   314.2  467.74   326.1  471.58     334  476.95     338  478.18
  355.06479.5282   405.4  481.46   425.2  486.52  434.27487.6288     445  487.61
#Mann= 8 ,-1 , 0
       0     .12       0  145.71     .06       0  175.88    .016       0
  206.04     .12       0   246.8    .045       0   271.6     .12       0
  355.06     .08       0  434.27     .06       0
Bank Sta=246.8,271.6
XS Rating Curve= 0 ,0
Exp/Cntr=0.3,0.1

Type RM Length L Ch R = 1 ,3287.8  ,214.4,195.8,175.4
XS GIS Cut Line= 3
     2306344.152      409491.852     2306438.553      409411.557
     2306747.798      409341.027
#Sta/Elev= 30
       0  522.27      36  508.45      56  496.12      68  489.99      76  482.84
      80  480.54   147.7  448.38   159.6  444.84   167.5  444.66   176.8445.8333
   195.3  446.41   219.1  444.62     227  445.01  231.96443.8049   233.6  443.13
   242.9  441.82   250.8  441.93   258.7  443.72   274.6  444.29   282.5  445.72
   298.4  452.76     338  460.06   369.8  472.29  384.42473.7522  393.95474.2714
   401.5  475.03   409.4  478.59   417.3  480.94  431.33482.6403   441.1  483.92
#Mann= 8 ,-1 , 0
       0     .12       0   176.8    .016       0  231.96     .12       0
   233.6    .045       0   258.7     .12       0  384.42     .08       0
  393.95     .12       0  431.33    .016       0
#XS Ineff= 2 , 0
           188.7  449.95
Permanent Ineff=
       F       F
Bank Sta=233.6,258.7
XS Rating Curve= 0 ,0
Exp/Cntr=0.3,0.1

Type RM Length L Ch R = 1 ,3092    ,227.9,228,228.1
XS GIS Cut Line= 3
     2306486.405      409661.557     2306598.384      409634.213
     2306791.092      409349.057
#Sta/Elev= 30
       0   501.1    27.8  491.68    59.6  483.25    83.5  477.92   115.3  467.76
     139  456.66  149.14  450.82   154.8  447.91   158.8   446.5   178.6  446.33
   194.4  445.21   198.3  444.03   202.3  441.47   206.3  439.71   210.2  439.29
     230  441.32   241.9  443.81   277.5  442.33   309.1     444  339.18  444.02
   356.6  443.98   360.5  445.32   364.5   448.4   372.4  457.84   376.4  461.36
   396.1  471.85  410.83477.8895   415.9  479.45   431.7  482.61   459.4  486.32
#Mann= 6 ,-1 , 0
       0     .12       0  149.14    .016       0   202.3    .045       0
     230     .12       0  339.18    .016       0  410.83     .12       0
Bank Sta=202.3,230
XS Rating Curve= 0 ,0
Exp/Cntr=0.3,0.1

Type RM Length L Ch R = 1 ,2864    ,353.6,352.2,347.7
XS GIS Cut Line= 4
     2306608.801      409824.317     2306755.936      409799.577
     2306960.593      409484.171     2306944.738      409399.838
#Sta/Elev= 30
       0  481.62    98.2  470.83   113.9  468.18  132.51461.4205   145.3  457.24
   165.2  455.39   181.2  452.04  187.86449.4492   193.2  446.66   197.2   446.2
   205.2  449.16   209.2  449.35   233.2  447.62   237.2  445.72  245.07439.6913
   253.2  438.43   261.2  438.81   265.2  440.14   277.2  441.76   289.2  441.18
   341.2  443.32   369.2  441.82   437.2  442.26   485.2  441.67   493.2  443.78
   501.2  449.31   513.2   451.2     533  456.06   575.9  470.95     611  479.62
#Mann= 5 ,-1 , 0
       0     .12       0  132.51     .06       0  187.86    .016       0
  245.07    .045       0   265.2     .12       0
Bank Sta=245.07,265.2
XS Rating Curve= 0 ,0
Exp/Cntr=0.3,0.1