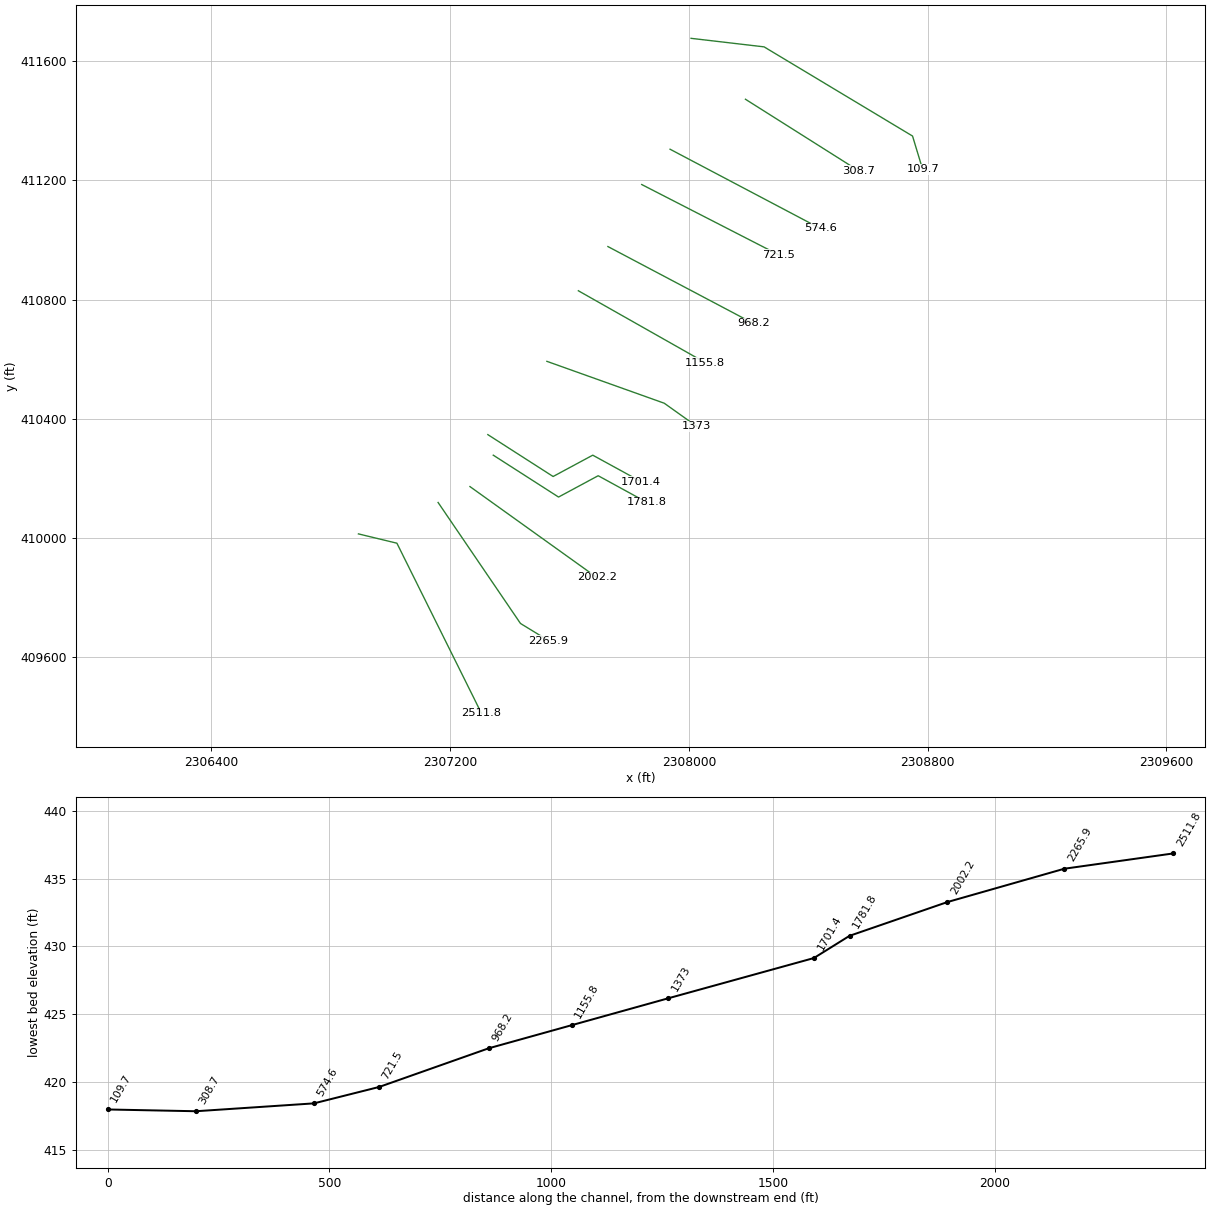
HEC-RAS study LONGHOLLOW.prj: LONGHOLLOW

--- LONGHOLLOW.g01 (geometry) --- (continued)

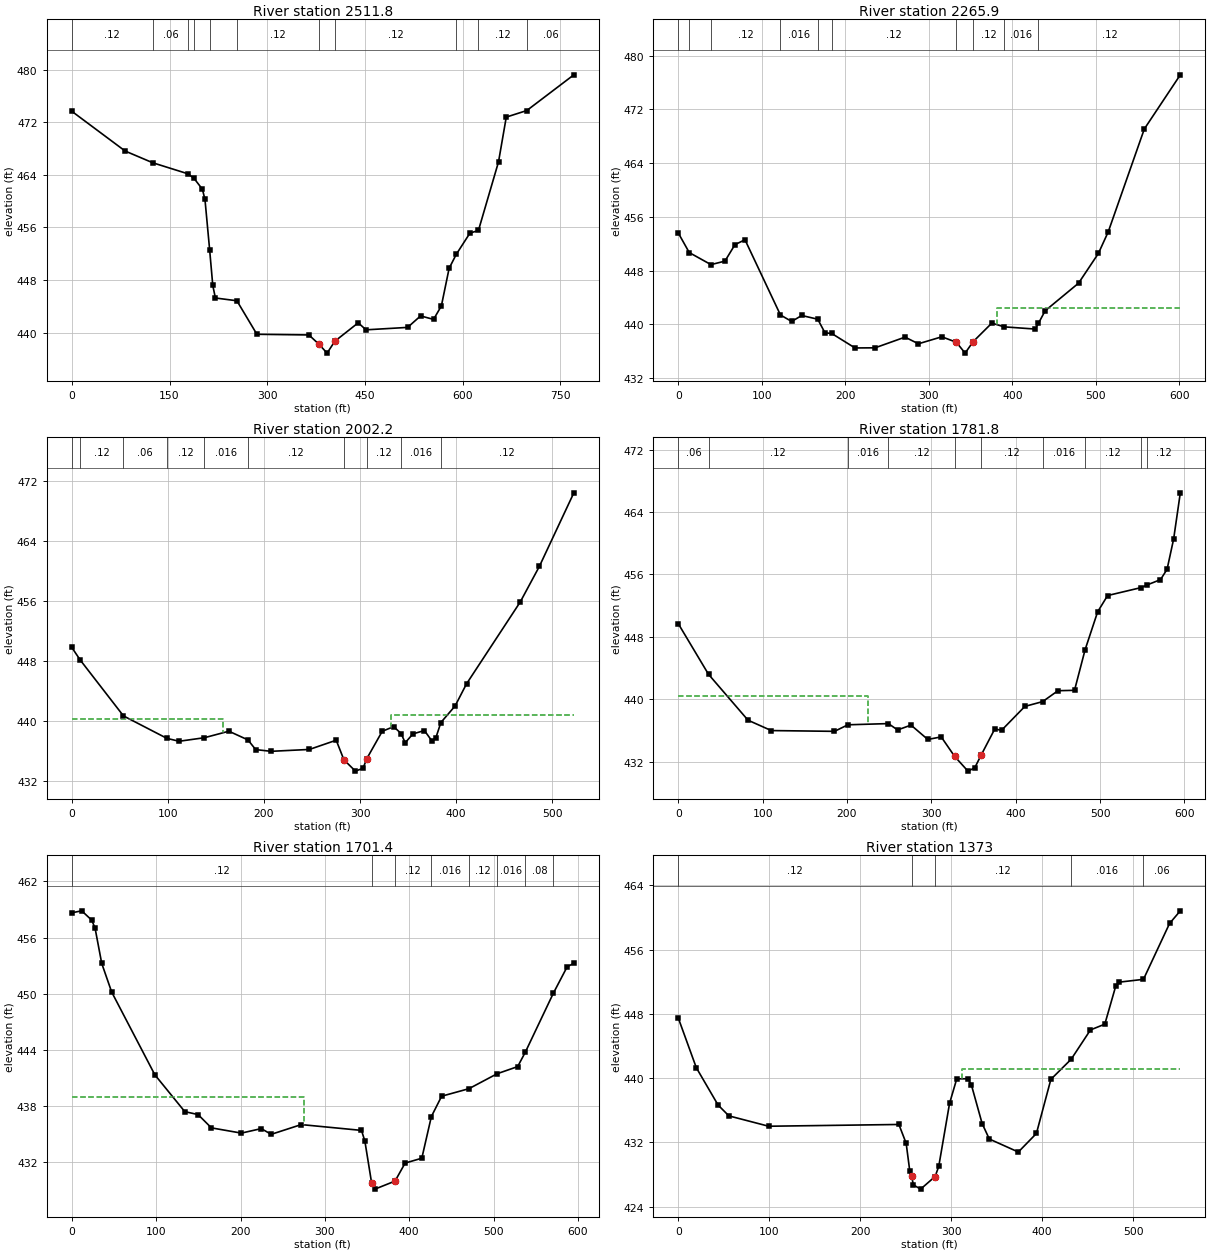
Type RM Length L Ch R = 1 ,2511.8  ,241.8,245.9,248.1
XS GIS Cut Line= 3
     2306892.655      410013.119     2307021.561      409981.869
      2307304.96      409410.419
#Sta/Elev= 30
       0  473.71    81.9  467.65  124.45465.8554  178.36464.1789   187.6463.4879
   200.4  461.84   204.4  460.28  211.59452.5947   216.4  447.17   220.4  445.26
  253.39444.8375   284.1  439.73   363.9  439.63   379.6  438.19   391.8  436.86
   403.7  438.67   439.6  441.48   451.6  440.41   515.4  440.78   535.3  442.53
   555.2     442   567.2  444.05   579.1  449.78  590.03451.9068     611  455.14
   624.1455.5518   654.9     466   666.8  472.82  698.29 473.819   770.5  479.26
#Mann= 11 ,-1 , 0
       0     .12       0  124.45     .06       0  178.36     .08       0
   187.6     .12       0  211.59    .016       0  253.39     .12       0
   379.6    .045       0   403.7     .12       0  590.03    .016       0
   624.1     .12       0  698.29     .06       0
Bank Sta=379.6,403.7
XS Rating Curve= 0 ,0
Exp/Cntr=0.3,0.1

Type RM Length L Ch R = 1 ,2265.9  ,255.2,263.7,290.9
XS GIS Cut Line= 3
     2307159.582      410118.588     2307435.624      409712.338
     2307529.374      409655.046
#Sta/Elev= 30
       0  453.62   13.19450.6928   39.18448.8996    55.9  449.42    67.9  451.87
    79.9   452.6  122.33441.4099   135.8  440.44   147.8  441.33  166.99440.7768
   175.7  438.74  183.58438.6652   211.6   436.5   235.6  436.52   271.5  438.11
   287.5  437.12   315.5  438.16   332.9  437.35   343.4  435.73   352.9  437.42
   375.4   440.2  390.06439.6409   427.3  439.31  431.18440.1636   439.2  442.03
   479.2  446.14   502.9  450.56   514.7  453.77   557.9  469.08     601  477.14
#Mann= 10 ,-1 , 0
       0     .08       0   13.19     .06       0   39.18     .12       0
  122.33    .016       0  166.99     .08       0  183.58     .12       0
   332.9    .045       0   352.9     .12       0  390.06    .016       0
  431.18     .12       0
#XS Ineff= 2 , 0
                             381           442.5
Permanent Ineff=
       F       F
Bank Sta=332.9,352.9
XS Rating Curve= 0 ,0
Exp/Cntr=0.3,0.1

Type RM Length L Ch R = 1 ,2002.2  ,181.3,220.4,251.5
XS GIS Cut Line= 2
     2307266.353      410171.973     2307690.832      409867.286
#Sta/Elev= 30
       0  449.76    8.85448.0679   53.79 440.631   99.01437.6362   111.7  437.25
  138.06437.7231   163.5  438.59  183.32 437.433   191.4  436.14   207.4  435.91
   247.3  436.16   275.2  437.39   283.2  434.78   295.2  433.27   303.1  433.65
   307.1  434.95   323.1  438.58     335   439.2  342.73438.2786     347  437.05
     355  438.23     367  438.68   374.9  437.27   378.9  437.71  384.13439.7491
   398.9  441.95   410.8   444.9   466.7  455.81   486.6  460.55   522.5  470.36
#Mann= 10 ,-1 , 0
       0     .06       0    8.85     .12       0   53.79     .06       0
   99.01     .12       0  138.06    .016       0  183.32     .12       0
   283.2    .045       0   307.1     .12       0  342.73    .016       0
  384.13     .12       0
#XS Ineff= 2 , 0
          157.89  440.16  331.96          440.79
Permanent Ineff=
       F       F
Bank Sta=283.2,307.1
XS Rating Curve= 0 ,0
Exp/Cntr=0.3,0.1

Type RM Length L Ch R = 1 ,1781.8  ,89,80.4,94.1
XS GIS Cut Line= 4
     2307344.478      410277.442     2307563.228      410136.817
      2307696.04      410208.432     2307857.499       410119.89
#Sta/Elev= 30
       0  449.69   35.92443.1874    82.7  437.31   110.3  435.98   185.2  435.88
  201.13436.7197  249.08436.8744     260  436.06   275.9  436.68   295.8  434.84
   311.7  435.17   327.6  432.67   343.4  430.78   351.4   431.2   359.3  432.89
   375.2  436.19   383.2  436.01   410.9  439.08  431.91439.6919   450.1  441.09
   469.7  441.14  482.23446.3395   497.1   451.2   508.9  453.29  548.96454.3197
  555.73454.6513   571.6  455.33   579.4  456.65   587.2  460.55   595.1  466.46
#Mann= 10 ,-1 , 0
       0     .06       0   35.92     .12       0  201.13    .016       0
  249.08     .12       0   327.6    .045       0   359.3     .12       0
  431.91    .016       0  482.23     .12       0  548.96     .08       0
  555.73     .12       0
#XS Ineff= 2 , 0
           224.9  440.46
Permanent Ineff=
       F       F
Bank Sta=327.6,359.3
XS Rating Curve= 0 ,0
Exp/Cntr=0.3,0.1

Type RM Length L Ch R = 1 ,1701.4  ,348.9,328.4,288.8
XS GIS Cut Line= 4
     2307326.249      410346.452     2307544.999      410205.827
     2307677.811      410277.442     2307839.269        410188.9
#Sta/Elev= 30
       0  458.64    11.8  458.85    23.6  457.86    27.6  457.01    35.5  453.24
    47.3  450.18    98.5  441.34     134  437.41   149.7   437.1   165.5  435.68
     201  435.12   224.6   435.6   236.4  434.99     272  436.03   343.4  435.41
   347.4  434.27   355.4   429.8   359.3  429.14   383.2     430   395.1  431.92
   414.9  432.44  426.22 436.886   438.4  439.06  470.77439.8627  504.13441.4565
   528.5  442.22   537.5443.7439  570.86450.0644   587.2  452.88   595.1  453.25
#Mann= 8 ,-1 , 0
       0     .12       0   355.4    .045       0   383.2     .12       0
  426.22    .016       0  470.77     .12       0  504.13    .016       0
   537.5     .08       0  570.86     .12       0
#XS Ineff= 2 , 0
          274.97  438.93
Permanent Ineff=
       F       F
Bank Sta=355.4,383.2
XS Rating Curve= 0 ,0
Exp/Cntr=0.3,0.1

Type RM Length L Ch R = 1 ,1373    ,221.4,217.2,212.7
XS GIS Cut Line= 3
     2307524.165      410592.546     2307917.394      410451.921
     2308026.769      410373.796
#Sta/Elev= 30
       0  447.49    19.9  441.28    43.8  436.64    55.7  435.29    99.4     434
   242.6  434.22   250.6  431.87   254.6   428.4  256.48  427.86   258.5   426.7
   266.5  426.17   282.4  427.74   286.4  428.99   298.3  436.85   306.2   439.9
   318.2  439.91   322.2  439.19   334.1  434.34     342  432.41   373.9  430.79
   393.8   433.1   409.7  439.84  432.02442.3456   453.2  445.99     469  446.71
   480.9  451.41   484.8  451.94  511.49452.2902   540.2  459.25     552  460.82
#Mann= 5 ,-1 , 0
       0     .12       0  256.48    .045       0   282.4     .12       0
  432.02    .016       0  511.49     .06       0
#XS Ineff= 2 , 0
                          311.94          441.07
Permanent Ineff=
       F       F
Bank Sta=256.48,282.4
XS Rating Curve= 0 ,0
Exp/Cntr=0.3,0.1

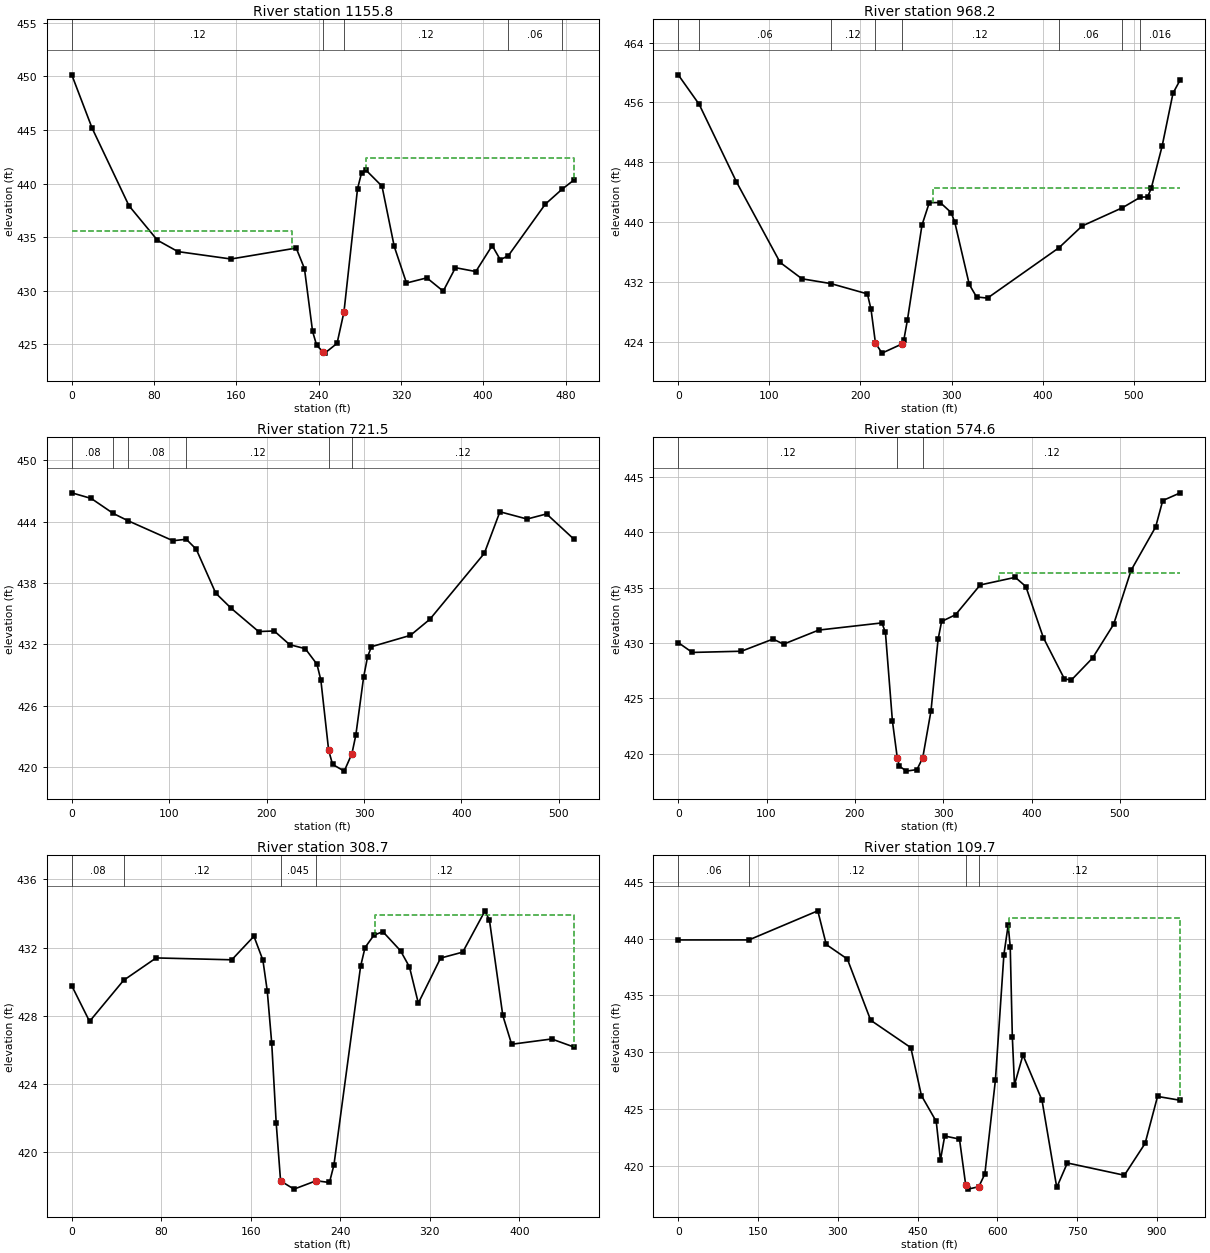
Type RM Length L Ch R = 1 ,1155.8  ,186.4,187.6,188.2
XS GIS Cut Line= 2
     2307629.634      410829.525     2308054.113       410588.64
#Sta/Elev= 30
       0  450.15    19.8  445.17    55.6  437.94    83.3  434.72   103.2  433.66
   154.8  432.97   218.2  433.99   226.2  432.08   234.1  426.22   238.1  424.91
   244.6  424.29     246  424.19   257.9   425.1   264.6  428.02   277.8  439.52
   281.7     441   285.7  441.29   301.6  439.76   313.5  434.14   325.4  430.73
   345.2  431.21   361.1  429.97     373  432.16   392.8   431.8   408.7  434.22
   416.6   432.9   424.4433.2775   460.3  438.08  476.86439.4972   488.1  440.33
#Mann= 5 ,-1 , 0
       0     .12       0   244.6    .045       0   264.6     .12       0
   424.4     .06       0  476.86     .12       0
#XS Ineff= 2 , 0
          214.38  435.54  285.62          442.41
Permanent Ineff=
       F       F
Bank Sta=244.6,264.6
XS Rating Curve= 0 ,0
Exp/Cntr=0.3,0.1

Type RM Length L Ch R = 1 ,968.2   ,246.3,246.6,246.4
XS GIS Cut Line= 2
     2307728.592      410977.963     2308215.572       410720.15
#Sta/Elev= 30
       0   459.7      23455.7475    63.9  445.38   111.8  434.61   135.8  432.42
  167.57 431.778   207.6   430.4   211.6  428.32  216.43  423.83   223.6  422.48
   245.1  423.68   247.6  424.25   251.6  426.97   267.5  439.61   275.5   442.6
   287.5  442.62   299.5  441.28   303.5  439.98   319.4  431.66   327.4  429.99
   339.4  429.84  417.84436.5745   443.2  439.48  487.51441.9272  507.22443.3388
   515.1  443.37   519.1  444.53     531  450.14     543  457.25     551  459.05
#Mann= 8 ,-1 , 0
       0     .12       0      23     .06       0  167.57     .12       0
  216.43    .045       0   245.1     .12       0  417.84     .06       0
  487.51     .12       0  507.22    .016       0
#XS Ineff= 2 , 0
                          279.59          444.54
Permanent Ineff=
       F       F
Bank Sta=216.43,245.1
XS Rating Curve= 0 ,0
Exp/Cntr=0.3,0.1

Type RM Length L Ch R = 1 ,721.5   ,147.2,147,146.7
XS GIS Cut Line= 2
     2307841.874      411186.296     2308300.207      410950.619
#Sta/Elev= 30
       0  446.81      20  446.26   42.55444.7978   57.61444.0901   103.9  442.13
  117.53 442.277   127.8   441.3   147.8  437.01   163.8  435.52   191.8  433.26
   207.8  433.32   223.7  431.98   239.7  431.59   251.7  430.07   255.7  428.52
   263.7  421.66   267.7  420.29   279.7  419.63   287.6  421.34   291.6  423.15
   299.6  428.81   303.6  430.78   307.6  431.78   347.6  432.89   367.6  434.46
   423.5   440.9   439.5  444.96   467.4  444.25   487.4  444.75   515.4  442.29
#Mann= 6 ,-1 , 0
       0     .08       0   42.55     .12       0   57.61     .08       0
  117.53     .12       0   263.7    .045       0   287.6     .12       0
Bank Sta=263.7,287.6
XS Rating Curve= 0 ,0
Exp/Cntr=0.3,0.1

Type RM Length L Ch R = 1 ,574.6   ,267,265.9,264.4
XS GIS Cut Line= 2
     2307936.926      411304.786      2308439.53      411039.161
#Sta/Elev= 30
       0  430.04    15.9  429.15    71.6  429.26   107.3  430.36   119.3   429.9
     159  431.17   230.6  431.82   234.6  430.96   242.5  422.96  248.01  419.63
   250.4  418.87   258.4  418.42   270.3  418.56   276.8  419.61   286.2  423.87
   294.2  430.32   298.2  431.95     314  432.56   341.9  435.25   381.6  435.94
   393.6  435.11   413.4  430.49   437.3  426.75   445.2  426.66   469.1  428.64
     493  431.69   512.8  436.58   540.6   440.5   548.6  442.88   568.5  443.58
#Mann= 3 ,-1 , 0
       0     .12       0  248.01    .045       0   276.8     .12       0
#XS Ineff= 2 , 0
                          362.77          436.35
Permanent Ineff=
       F       F
Bank Sta=248.01,276.8
XS Rating Curve= 0 ,0
Exp/Cntr=0.3,0.1

Type RM Length L Ch R = 1 ,308.7   ,199,199,199
XS GIS Cut Line= 2
     2308189.522      411472.627     2308568.618      411232.556
#Sta/Elev= 30
       0  429.76    15.9  427.67   46.33430.0779    75.4  431.39     143  431.28
   162.8  432.66   170.8  431.26   174.7  429.46   178.7  426.39   182.7  421.71
   186.6  418.32   198.6  417.84   218.4  418.33   230.3  418.23   234.3  419.26
   258.1  430.89   262.1     432     270  432.72     278  432.93   293.8  431.81
   301.8  430.86   309.7  428.74   329.6  431.38   349.4  431.73   369.3  434.15
   373.3  433.59   385.2  428.02   393.1  426.33   428.9  426.64   448.7  426.17
#Mann= 4 ,-1 , 0
       0     .08       0   46.33     .12       0   186.6    .045       0
   218.4     .12       0
#XS Ineff= 2 , 0
                          270.86          433.91
Permanent Ineff=
       F       F
Bank Sta=186.6,218.4
XS Rating Curve= 0 ,0
Exp/Cntr=0.3,0.1

Type RM Length L Ch R = 1 ,109.7   ,111,109.7,108.4
XS GIS Cut Line= 4
     2308007.238      411677.182      2308252.03      411648.536
     2308749.426      411349.057      2308783.28      411237.077
#Sta/Elev= 30
       0  439.88  132.96 439.882   262.4  442.44   278.3  439.48     318   438.2
   361.8  432.82   437.3  430.41   457.2   426.2   485.1  423.92     493  420.52
     501  422.64   528.8  422.37   540.6   418.3   544.7  417.97   565.1  418.18
   576.5   419.3   596.4  427.58   612.3  438.59   620.3  441.18   624.2   439.3
   628.2  431.31   632.2  427.14   648.1  429.76   683.9   425.8   711.7  418.12
   731.6  420.27   838.8  419.19   877.8  421.99   901.2  426.12     944  425.78
#Mann= 4 ,-1 , 0
       0     .06       0  132.96     .12       0   540.6    .045       0
   565.1     .12       0
#XS Ineff= 2 , 0
                          621.31          441.82
Permanent Ineff=
       F       F
Bank Sta=540.6,565.1
XS Rating Curve= 0 ,0
Exp/Cntr=0.3,0.1

Chan Stop Cuts=-1
Use User Specified Reach Order=0
Composite Channel Slope=5